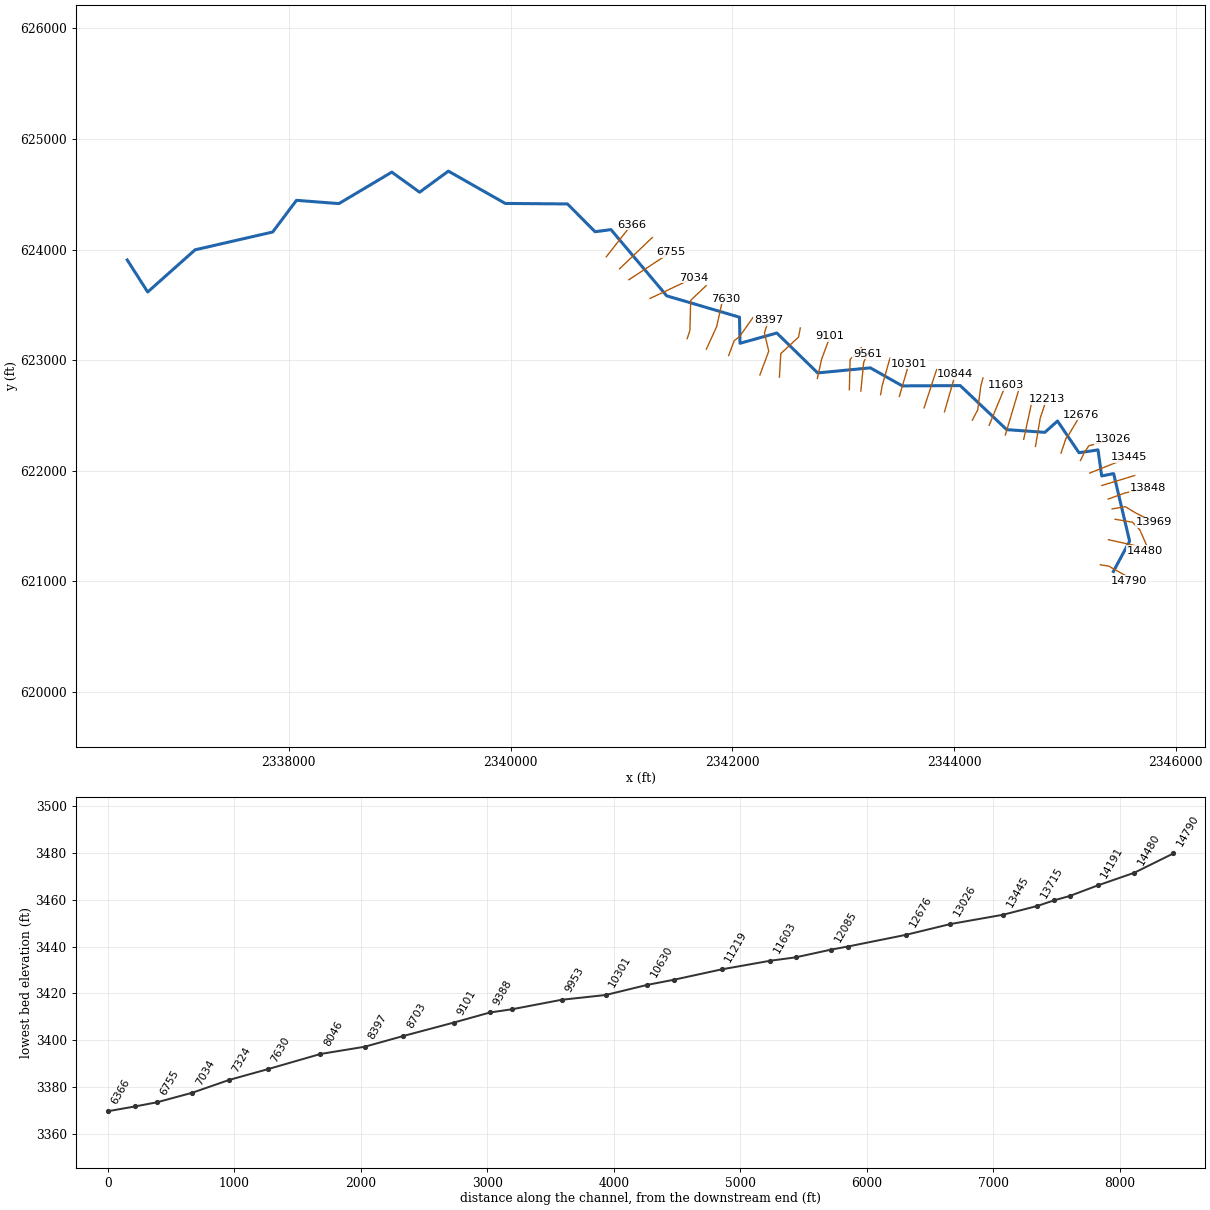
--- ELKRN.prj (project) ---

Proj Title=ELKRN
Current Plan=p01
Default Exp/Contr=0,0
English Units
Geom File=g01
Flow File=f01
Plan File=p01
BEGIN DESCRIPTION:
----------MODEL BY WOOD PLC 2022----------
AFH study
Randolph County, WV
HEC-RAS Version: RAS 6.2
Vertical Datum: NAVD88
Projection: NAD 1983 StatePlane West Virginia S FIPS 4702 (US Feet)
Terrain: 1-meter LIDAR (FEMA Region III 3DEP collected 2016-2018)
Land Use: 2019 NLCD
Hydrologic Method:
WV SIR2010-5033 regression equations
Additional Model Notes:
None
END DESCRIPTION:
DSS Export Rating Curves= 0
DSS Export Rating Curve Sorted= 0
DSS Export Volume Flow Curves= 0
DXF OffsetX= 0
DXF OffsetY= 0
DXF ScaleX= 0
DXF ScaleY= 0

--- ELKRN.p01 (plan) ---

Plan Title=Floodplain
Program Version=6.20
Short Identifier=Floodplain
Geom File=g01
Flow File=f01
Subcritical Flow
K Sum by GR= 0
Std Step Tol= 0.01
Critical Tol= 0.01
Num of Std Step Trials= 20
Max Error Tol= 0.3
Flow Tol Ratio= 0.001
Split Flow NTrial= 30
Split Flow Tol= 0.02
Split Flow Ratio= 0.02
Log Output Level= 0
Friction Slope Method= 1
Unsteady Friction Slope Method= 2
Unsteady Bridges Friction Slope Method= 1
Parabolic Critical Depth
Global Vel Dist= 0 , 0 , 0
Global Log Level= 0
CheckData=True
Encroach Param=-1 ,0,0, 0
Mapping Interval=1HOUR
Computation Time Step Use Courant=        0
Computation Time Step Use Time Series=    0
Computation Time Step Count To Double=0
Computation Time Step Max Doubling=0
Computation Time Step Max Halving=0
Computation Time Step Residence Courant=0
Run HTab= 0
Run UNet= 0
Run Sediment= 0
Run PostProcess= 0
Run WQNet= 0
Run RASMapper=-1
UNET Theta= 0
UNET Theta Warmup= 0
UNET ZTol= 0
UNET ZSATol= 0
UNET MxIter= 0
UNET Max Iter WO Improvement= 0
UNET MaxInSteps= 0
UNET DtIC= 0
UNET DtMin= 0
UNET MaxCRTS= 0
UNET WFStab= 0
UNET SFStab= 0
UNET WFX= 1
UNET SFX= 1
UNET Gravity=32.174
UNET 1D Methodology=Finite Difference
UNET DSS MLevel= 1
UNET Pardiso=0
UNET DZMax Abort= 0
UNET Use Existing IB Tables= 0
UNET Froude Reduction=False
UNET Froude Limit= 0
UNET Froude Power= 0
UNET D1 Cores= 0
UNET WindReference=Eulerian
UNET WindDragFormulation=Hsu (1988)
UNET D2 Coriolis=0
UNET D2 Cores= 0
UNET D2 Theta= 1
UNET D2 Theta Warmup= 1
UNET D2 Z Tol= 0.01
UNET D2 Volume Tol= 0.01
UNET D2 Max Iterations= 20
UNET D2 Equation= 0
UNET D2 RampUpFraction=0.1
UNET D2 TimeSlices= 1
UNET D2 Turbulence Formulation=Non-Conservative (original)
UNET D2 Eddy Viscosity=0.3
UNET D2 Transverse Eddy Viscosity=0.1
UNET D2 Smagorinsky Mixing=0
UNET D2 BCVolumeCheck=0
UNET D2 Cores=0
UNET D2 SolverType=PARDISO (Direct)
UNET D2 Minimum Iterations= 2147483647
UNET D2 Maximum Iterations= 2147483647
UNET D2 Restart Number= 10
UNET D2 Relaxation Coeff=1.3
UNET D2 SOR Precondition Iterations= 10
UNET D2 ILUT Maximum Fill= 8
UNET D2 ILUT Tolerance=1E-08
UNET D1D2 MaxIter= 0
UNET D1D2 ZTol=0.01
UNET D1D2 QTol=0.1
UNET D1D2 MinQTol=1
Write IC File= 0
Write IC File at Fixed DateTime=0
Write IC File at Sim End=0
Echo Input=False
Echo Parameters=False
Echo Output=False
Write Detailed= 0
HDF Write Warmup=0
HDF Write Time Slices=0
HDF Flush=0
HDF Compression= 1
HDF Chunk Size= 1
HDF Spatial Parts= 1
HDF Use Max Rows=0
HDF Fixed Rows= 1
Calibration Method= 0
Calibration Iterations= 20
Calibration Max Change=0.05
Calibration Tolerance=0.2
Calibration Maximum=1.5
Calibration Minimum=0.5
Calibration Optimization Method= 1
WQ AD Non Conservative
WQ ULTIMATE=-1
WQ Max Comp Step=1HOUR
WQ Output Interval=15MIN
WQ Output Selected Increments= 0
WQ Output face flow=0
WQ Output face velocity=0
WQ Output face area=0
WQ Output face dispersion=0
WQ Output cell volume=0
WQ Output cell surface area=0
WQ Output cell continuity=0
WQ Output cumulative cell continuity=0
WQ Output face conc=0
WQ Output face dconc_dx=0
WQ Output face courant=0
WQ Output face peclet=0
WQ Output face adv mass=0
WQ Output face disp mass=0
WQ Output cell mass=0
WQ Output cell source sink temp=0
WQ Output nsm pathways=0
WQ Output nsm derived pathways=0
WQ Create Restart=0
WQ Fixed Restart=0
WQ System Summary=0
WQ Write To DSS=0
Sorting and Armoring Iterations= 10
XS Update Threshold= 0.02
Bed Roughness Predictor= 0
Hydraulics Update Threshold= 0.02
Energy Slope Method= 1
Volume Change Method= 1
Sediment Retention Method= 0
Sediment TS Multiplier= 1
Warm Up Method= 0
XS Weighting Method= 0
Number of US Weighted Cross Sections= 1
Number of DS Weighted Cross Sections= 1
Upstream XS Weight=0
Main XS Weight=1
Downstream XS Weight=0
Number of DS XS's Weighted with US Boundary= 1
Upstream Boundary Weight= 1
Weight of XSs Associated with US Boundary= 0
Number of US XS's Weighted with DS Boundary= 1
Downstream Boundary Weight= 0.5
Weight of XSs Associated with DS Boundary= 0.5
Percentile Method= 0
Sediment Output Level= 3
Mass or Volume Output= 0
Output Increment Type= 1
Profile and TS Output Increment= 1
Transport Output Increment 1
XS Output Flag= 0
XS Output Increment= 10
Read HDF5 Sediment Hotstart= 0
Sediment Hotstart Type= 0
Write Gradation File= 0
Read Gradation Hotstart= 0
Write HDF5 File= 1
Write Binary Output= 1
Write DSS Sediment File= 0
DSS Sediment Output Type= 1
SV Curve= 0
Specific Gage Flag= 0
Subcell Erosion Methods= 0
Subcell Deposition Methods= 0
Advection Scheme= 1
Matrix Solver= 0
Implicit Weighting Factor= 1
Maximum Outer Loop Convergence Iterations= 5
Convergence Maximum Absolute= 0.001
Convergence RMSE= 0.0001
Grain Fractions Max Abs Error= 0.001
Max Subgrid Regions= 1
Max Subgrid Length Scale= 3.402823E+38
Initial Layer Thickness= 3.402823E+38
Min Layer Thickness= 3.402823E+38
Max Layer Thickness= 3.402823E+38
Number of Layers= 5

--- ELKRN.f01 (steady flow) ---

Flow Title=Flow
Program Version=4.00
Number of Profiles=1
Profile Names=P100yr
River Rch & RM=ELKRN,Main,14790
     468
River Rch & RM=ELKRN,Main,8703
     565
River Rch & RM=ELKRN,Main,5045
     628
Boundary for River Rch & Prof#=ELKRN,Main      ,1
Up Type=0
Dn Type=3
Dn Slope=0.006935

--- ELKRN.g01 (geometry) ---

Geom Title=Geometry
Program Version=6.20

River Reach=ELKRN           ,Main
Reach XY= 30
2345438.31357497621089.2195951522345584.77700004621362.436000004
2345440.67300001 621974.348000022345332.99600001621952.694000021
2345299.92299998622188.3710000222345128.04800001622162.849999994
2344934.29800002622449.5690000212344820.49600002622347.225000009
     2344475.965622371.4440000212344056.66500005622769.797999993
2343533.77700004622767.2769999952343245.75599998622930.298000008
2342770.23600003622884.4650000042342402.04099999623245.305999994
2342070.09700003623152.2500000152342065.23600003623388.361000016
2341408.82344011 623581.49676042     2340905.883624180.075000003
2340762.39300002624161.3250000182340513.41300003624412.453000009
2339952.26075541624416.8951996482339438.94300003624709.068000004
     2339179.433624518.580000013       2338928.7624700.075000018
2338451.32600001624415.4500000032338068.67400002624445.127000019
2337854.26700002624158.7150000042337153.96100001623997.591999993
2336726.32492898 623616.182360972336542.07600495623905.761645817

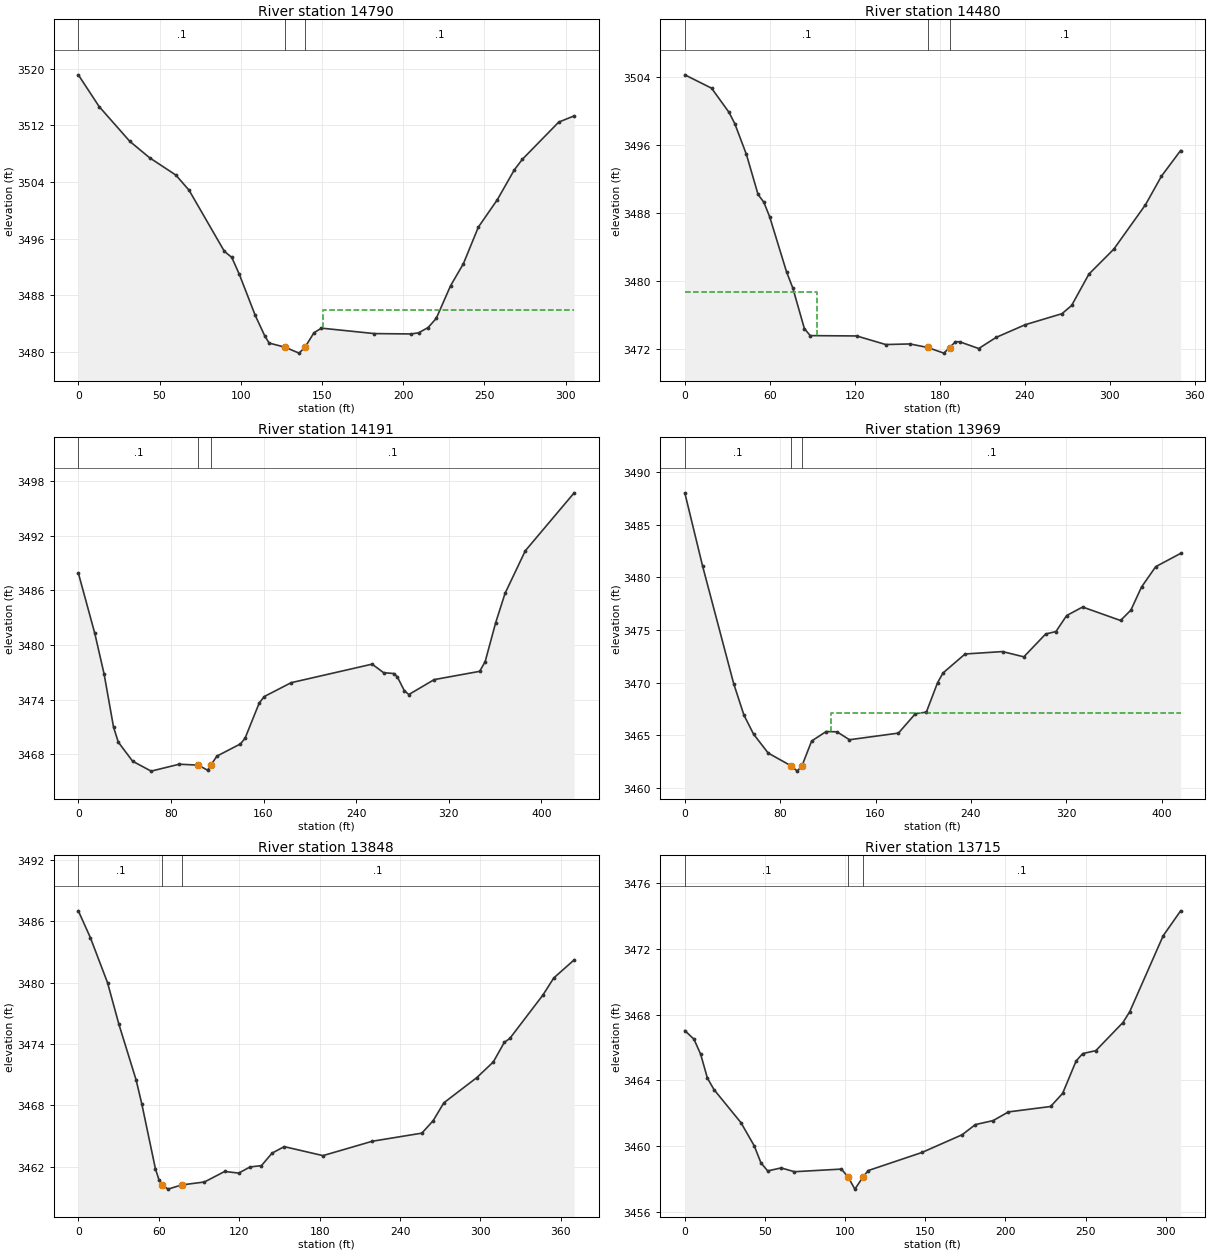
Type RM Length L Ch R = 1 ,14790   ,300.2,309.3,308.4
XS GIS Cut Line= 4
2345320.90250575621149.8713588082345397.34163438621137.248383436
2345548.11606243621051.6926614762345578.97222445621006.810971267
#Sta/Elev= 30
       0 3519.15    12.8 3514.67    31.7 3509.75    43.9 3507.43    60.1 3504.98
    68.2 3502.84    89.9 3494.22    94.5 3493.35    99.1 3490.98   108.9 3485.18
   114.8 3482.26   117.5 3481.25   127.4 3480.66   135.9 3479.83  139.51 3480.65
   145.1 3482.71   149.7 3483.36   182.3 3482.59   204.9 3482.54   209.5  3482.7
   215.4 3483.45   220.4 3484.75   229.2 3489.35   237.1 3492.47   246.3 3497.63
     258 3501.51   268.4  3505.7   273.3 3507.19   295.8 3512.47   305.3 3513.35
#Mann= 3 ,-1,0
       0      .1       0   127.4    .045       0  139.51      .1       0
#XS Ineff= 1 ,-1
  150.37305.2968 3485.89
Permanent Ineff=
       F
Bank Sta=127.4,139.51
XS Rating Curve= 0 ,0
Exp/Cntr(USF)=0,0
Exp/Cntr=0.3,0.1

Type RM Length L Ch R = 1 ,14480   ,270.8,289.1,286.1
XS GIS Cut Line= 3
2345393.74516001621376.4063144332345685.46428865621311.522166604
2345721.79941143621275.706117002
#Sta/Elev= 30
       0 3504.29    18.9 3502.72    31.2 3499.88    35.3 3498.54    43.5 3494.92
    51.7 3490.22    55.8  3489.3    59.9 3487.59    71.8 3481.12    76.2 3479.23
    84.4 3474.44    88.5 3473.62   121.3 3473.58   141.8 3472.57   158.9 3472.64
  171.423472.224   182.8 3471.56   186.9 3472.22     191  3472.9   193.9  3472.9
   207.4  3472.1   219.7 3473.41   240.2  3474.9   266.2  3476.2     273 3477.17
   285.2 3480.86   302.7 3483.78   325.1 3489.01   336.4 3492.38   349.9 3495.39
#Mann= 3 ,-1,0
       0      .1       0  171.42    .045       0   186.9      .1       0
#XS Ineff= 2 , 0
           93.08 3478.77
Permanent Ineff=
       F       F
Bank Sta=171.42,186.9
XS Rating Curve= 0 ,0
Exp/Cntr(USF)=0,0
Exp/Cntr=0.3,0.1

Type RM Length L Ch R = 1 ,14191   ,216.2,222.1,222.6
XS GIS Cut Line= 4
2345454.18795281621561.270814616  2345611.626702 621534.37173184
2345677.29210995 621464.750576422345746.91326538621306.520677736
#Sta/Elev= 30
       0 3487.92    14.2 3481.29    22.3 3476.79    30.4 3470.99    34.5 3469.33
    46.9 3467.23    62.9 3466.14    87.2  3466.9  103.693466.799   111.6 3466.24
   114.53466.808   119.7 3467.79     140 3469.13     144 3469.75   156.2 3473.61
   160.5 3474.33   183.8 3475.86   253.8  3477.9   263.7 3476.96   272.5 3476.87
   275.5 3476.52   281.6 3474.98   285.5 3474.56   307.4  3476.2   346.7 3477.11
   351.4 3478.17   360.5 3482.45   368.6 3485.68   386.1 3490.36   428.3 3496.73
#Mann= 3 ,-1,0
       0      .1       0  103.69    .045       0   114.5      .1       0
Bank Sta=103.69,114.5
XS Rating Curve= 0 ,0
Exp/Cntr(USF)=0,0
Exp/Cntr=0.3,0.1

Type RM Length L Ch R = 1 ,13969   ,119.7,120.6,119.6
XS GIS Cut Line= 4
2345427.28887004621654.6264548392345545.96129405621675.196341668
2345636.94348579621619.8158771292345805.45832789 621534.37173184
#Sta/Elev= 30
       0 3488.03    14.9 3481.09      41 3469.92    49.6 3466.93    57.7 3465.12
    69.9 3463.33    89.5 3462.09    94.3 3461.61    98.3 3462.12   106.4 3464.47
   118.6 3465.37   127.7 3465.34   138.1 3464.59   179.2 3465.22   193.4 3467.06
   202.6 3467.21     212    3470   216.6 3470.93   235.1 3472.73   266.5 3472.96
   284.4 3472.46   302.7 3474.63   311.3 3474.86   320.3 3476.38   333.7 3477.19
   365.5 3475.91   374.2  3476.9   383.1 3479.09     395 3481.02   415.9 3482.28
#Mann= 3 ,-1,0
       0      .1       0    89.5    .045       0    98.3      .1       0
#XS Ineff= 2 , 0
                          122.95         3467.12
Permanent Ineff=
       F       F
Bank Sta=89.5,98.3
XS Rating Curve= 0 ,0
Exp/Cntr(USF)=0,0
Exp/Cntr=0.3,0.1

Type RM Length L Ch R = 1 ,13848   ,134.1,133.7,132.4
XS GIS Cut Line= 3
2345391.68714283621744.0263475962345540.42324759621797.824513148
2345746.91326538621844.502333259
#Sta/Elev= 30
       0 3487.04       9 3484.41    21.8    3480    30.3 3475.92    43.1 3470.49
    47.3 3468.17    57.5  3461.8    60.1 3460.73   62.673460.213    66.9  3459.8
    77.1 3460.21    94.1  3460.5   109.2 3461.53   119.6 3461.37   128.1 3461.97
   136.6  3462.1   144.5 3463.32   153.6 3463.96   182.5 3463.08   219.4 3464.49
   256.3 3465.28   264.7  3466.5   272.7 3468.25   297.3 3470.72   309.6 3472.25
   317.8 3474.17   321.9 3474.55   346.6  3478.8   354.7 3480.47   369.9 3482.24
#Mann= 3 ,-1,0
       0      .1       0   62.67    .045       0    77.1      .1       0
Bank Sta=62.67,77.1
XS Rating Curve= 0 ,0
Exp/Cntr(USF)=0,0
Exp/Cntr=0.3,0.1

Type RM Length L Ch R = 1 ,13715   ,266.5,270.2,266.1
XS GIS Cut Line= 2
2345334.72437931621866.6545190752345630.61428984621956.845561324
#Sta/Elev= 30
       0 3467.03     5.7 3466.51     9.9 3465.59    14.1 3464.14    18.2 3463.44
      35 3461.43    43.3 3460.02    47.5 3458.98    51.7 3458.49    60.1 3458.67
    68.4 3458.44    97.7  3458.6   101.9 3458.11   106.1 3457.38  111.193458.121
   114.4 3458.51   147.9 3459.61     173 3460.69   181.3 3461.31   192.3 3461.55
   201.9 3462.08   228.2 3462.41   235.7 3463.21   244.1 3465.18   248.2 3465.63
   256.4 3465.81   273.3 3467.52   277.5 3468.17   298.4  3472.8   309.3 3474.32
#Mann= 3 ,-1,0
       0      .1       0   101.9    .045       0  111.19      .1       0
Bank Sta=101.9,111.19
XS Rating Curve= 0 ,0
Exp/Cntr(USF)=0,0
Exp/Cntr=0.3,0.1

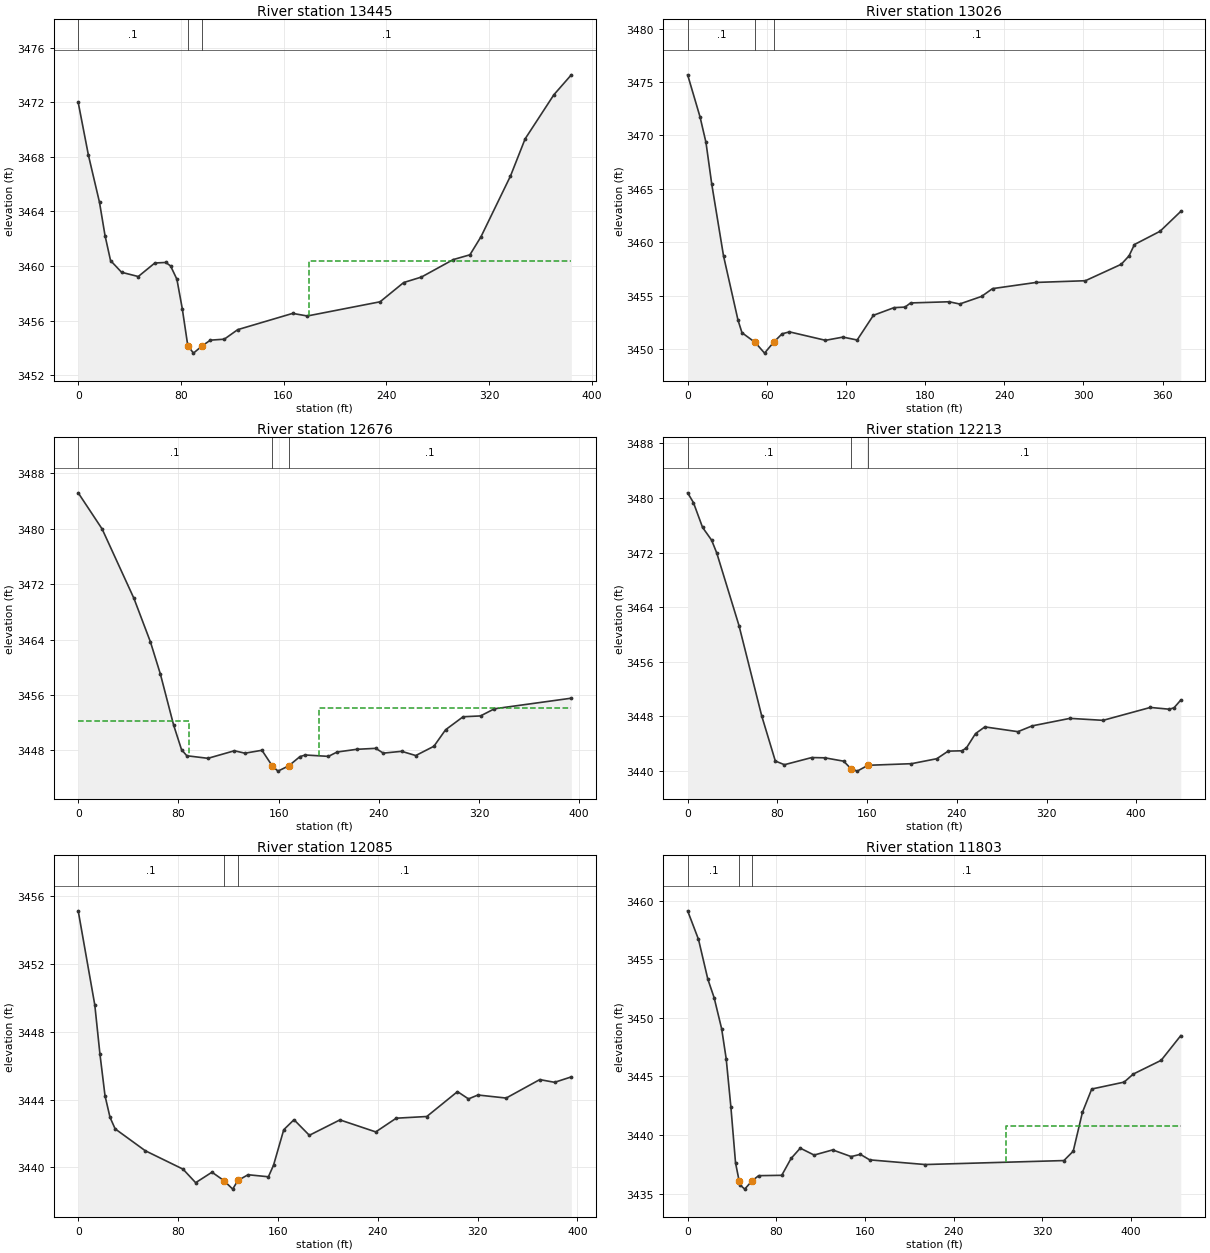
Type RM Length L Ch R = 1 ,13445   ,412.2,418.7,419.3
XS GIS Cut Line= 2
2345224.75459972 621978.997747142345581.56302125622121.404655955
#Sta/Elev= 30
       0 3471.98       8  3468.1    16.6 3464.66    20.9 3462.23    25.2  3460.4
    33.8 3459.54    46.8 3459.23    59.7 3460.22    68.3 3460.26      72    3460
    76.9 3459.03    81.1 3456.87   85.393454.164    89.8 3453.62    96.7 3454.16
     103 3454.57   113.8 3454.64   124.3 3455.34   167.1 3456.53   178.5 3456.34
   235.2 3457.38   253.6 3458.79   267.4 3459.19   292.2 3460.47   305.2 3460.82
   313.8 3462.14   336.8 3466.59   348.2 3469.31   370.6 3472.54   384.2    3474
#Mann= 3 ,-1,0
       0      .1       0   85.39    .045       0    96.7      .1       0
#XS Ineff= 1 ,-1
  179.72  404.583460.393
Permanent Ineff=
       F
Bank Sta=85.39,96.7
XS Rating Curve= 0 ,0
Exp/Cntr(USF)=0,0
Exp/Cntr=0.3,0.1

Type RM Length L Ch R = 1 ,13026   ,349.5,350.1,345.5
XS GIS Cut Line= 4
2345141.70259384622092.6679469052345175.98573855622163.871401312
2345216.42226822  622225.40525082345430.03263144622282.543825325
#Sta/Elev= 30
       0 3475.68     9.4 3471.74    13.9 3469.35    18.3 3465.43    27.2 3458.73
    38.2  3452.7    41.2 3451.53   51.223450.621    58.3 3449.62    65.2 3450.64
    71.6 3451.43    77.2 3451.61   104.5 3450.82   117.7 3451.12   128.5 3450.85
   140.8 3453.16   156.5 3453.88   164.8 3453.93     169 3454.32   198.2 3454.43
   206.2 3454.22   222.8 3454.93   231.1 3455.66   264.2 3456.24   301.5  3456.4
   328.7 3457.94   334.6 3458.73   338.7 3459.79   358.1 3461.03   373.8 3462.89
#Mann= 3 ,-1,0
       0      .1       0   51.22    .045       0    65.2      .1       0
Bank Sta=51.22,65.2
XS Rating Curve= 0 ,0
Exp/Cntr(USF)=0,0
Exp/Cntr=0.3,0.1

Type RM Length L Ch R = 1 ,12676   ,456.6,462.4,455.5
XS GIS Cut Line= 4
2344965.71072614622159.0460887932345010.72339993622292.213430244
 2345038.8531597622330.8918499222345143.46070383622507.581903452
#Sta/Elev= 30
       0  3485.2    19.1 3479.98    44.5 3469.96    57.7 3463.66    65.6 3459.04
    76.2 3451.66    82.5 3448.12    86.7 3447.24   103.6 3446.87   124.7 3447.96
   133.1 3447.61   146.7 3448.03   154.93445.784   159.5 3445.02   168.13445.784
     177 3447.11   181.3 3447.35   199.8 3447.15   206.7 3447.78   222.4 3448.17
   237.5 3448.31   243.6 3447.62   258.2 3447.88   269.5 3447.27     284 3448.61
   293.3 3450.99   307.3 3452.87   321.2 3452.99   332.3 3454.02   393.7 3455.55
#Mann= 3 ,-1,0
       0      .1       0   154.9    .045       0   168.1      .1       0
#XS Ineff= 2 , 0
           88.16 3452.27   191.9        3454.193
Permanent Ineff=
       F       F
Bank Sta=154.9,168.1
XS Rating Curve= 0 ,0
Exp/Cntr(USF)=0,0
Exp/Cntr=0.3,0.1

Type RM Length L Ch R = 1 ,12213   ,127.6,128.5,125
XS GIS Cut Line= 3
2344735.42437559622220.0431462822344778.27293043622475.488935205
2344835.41150495622646.904658779
#Sta/Elev= 30
       0 3480.76     5.2 3479.32    13.3  3475.7    21.4 3473.82      26 3471.93
    45.8 3461.31      66 3448.11    78.2 3441.47    86.3 3440.93   110.7 3441.98
   122.3 3441.94   139.1 3441.45   145.53440.369   151.2 3439.99   160.83440.845
   199.6 3441.08   222.2 3441.81   232.3 3442.92   244.5 3442.97   248.6 3443.39
   256.7 3445.49     265 3446.47   294.5 3445.77   307.2 3446.62   340.9 3447.72
   370.4 3447.43   412.6 3449.32   429.5 3449.06   433.7 3449.27   439.7  3450.4
#Mann= 3 ,-1,0
       0      .1       0   145.5    .045       0   160.8      .1       0
Bank Sta=145.5,160.8
XS Rating Curve= 0 ,0
Exp/Cntr(USF)=0,0
Exp/Cntr=0.3,0.1

Type RM Length L Ch R = 1 ,12085   ,278.8,282.2,275.8
XS GIS Cut Line= 2
 2344629.2135331622284.2140298112344713.07537941622670.294982598
#Sta/Elev= 30
       0 3455.15    13.3 3449.59    17.4  3446.7    21.5 3444.22    25.5 3442.95
    29.6 3442.27    53.7 3440.98      84 3439.89    94.1 3439.09   107.2 3439.71
  116.673439.218   123.8 3438.71   127.9 3439.22   136.1 3439.56   152.4 3439.44
   156.5 3440.12   164.7 3442.22   172.9 3442.81   185.2 3441.89   209.7  3442.8
   238.4 3442.09   254.8  3442.9   279.3    3443   303.9 3444.47   312.7 3444.04
   320.3 3444.27   342.9 3444.09   369.8 3445.18   381.7 3445.02   395.1 3445.34
#Mann= 3 ,-1,0
       0      .1       0  116.67    .045       0   127.9      .1       0
Bank Sta=116.67,127.9
XS Rating Curve= 0 ,0
Exp/Cntr(USF)=0,0
Exp/Cntr=0.3,0.1

Type RM Length L Ch R = 1 ,11803   ,195.3,199.6,194.3
XS GIS Cut Line= 2
2344463.86328898622323.7715044822344590.44720793622750.201081433
#Sta/Elev= 30
       0 3459.15     9.8 3456.71    18.2 3453.32    23.9 3451.73    30.7 3449.07
    34.8  3446.5      39 3442.41    43.2 3437.63    46.4 3436.11    47.4 3435.73
    51.5 3435.38   58.143436.096    64.1 3436.53    84.9 3436.56    93.3    3438
   101.6 3438.88   114.1 3438.29   130.8 3438.73   147.5 3438.16   155.8 3438.35
   164.2 3437.88   214.3 3437.48   339.4 3437.82   347.8 3438.62   356.1 3441.94
   364.5 3443.93   393.7 3444.52     402 3445.21   427.1 3446.38   444.8 3448.49
#Mann= 3 ,-1,0
       0      .1       0    46.4    .045       0   58.14      .1       0
#XS Ineff= 2 , 0
                          286.89          3440.8
Permanent Ineff=
       F       F
Bank Sta=46.4,58.14
XS Rating Curve= 0 ,0
Exp/Cntr(USF)=0,0
Exp/Cntr=0.3,0.1

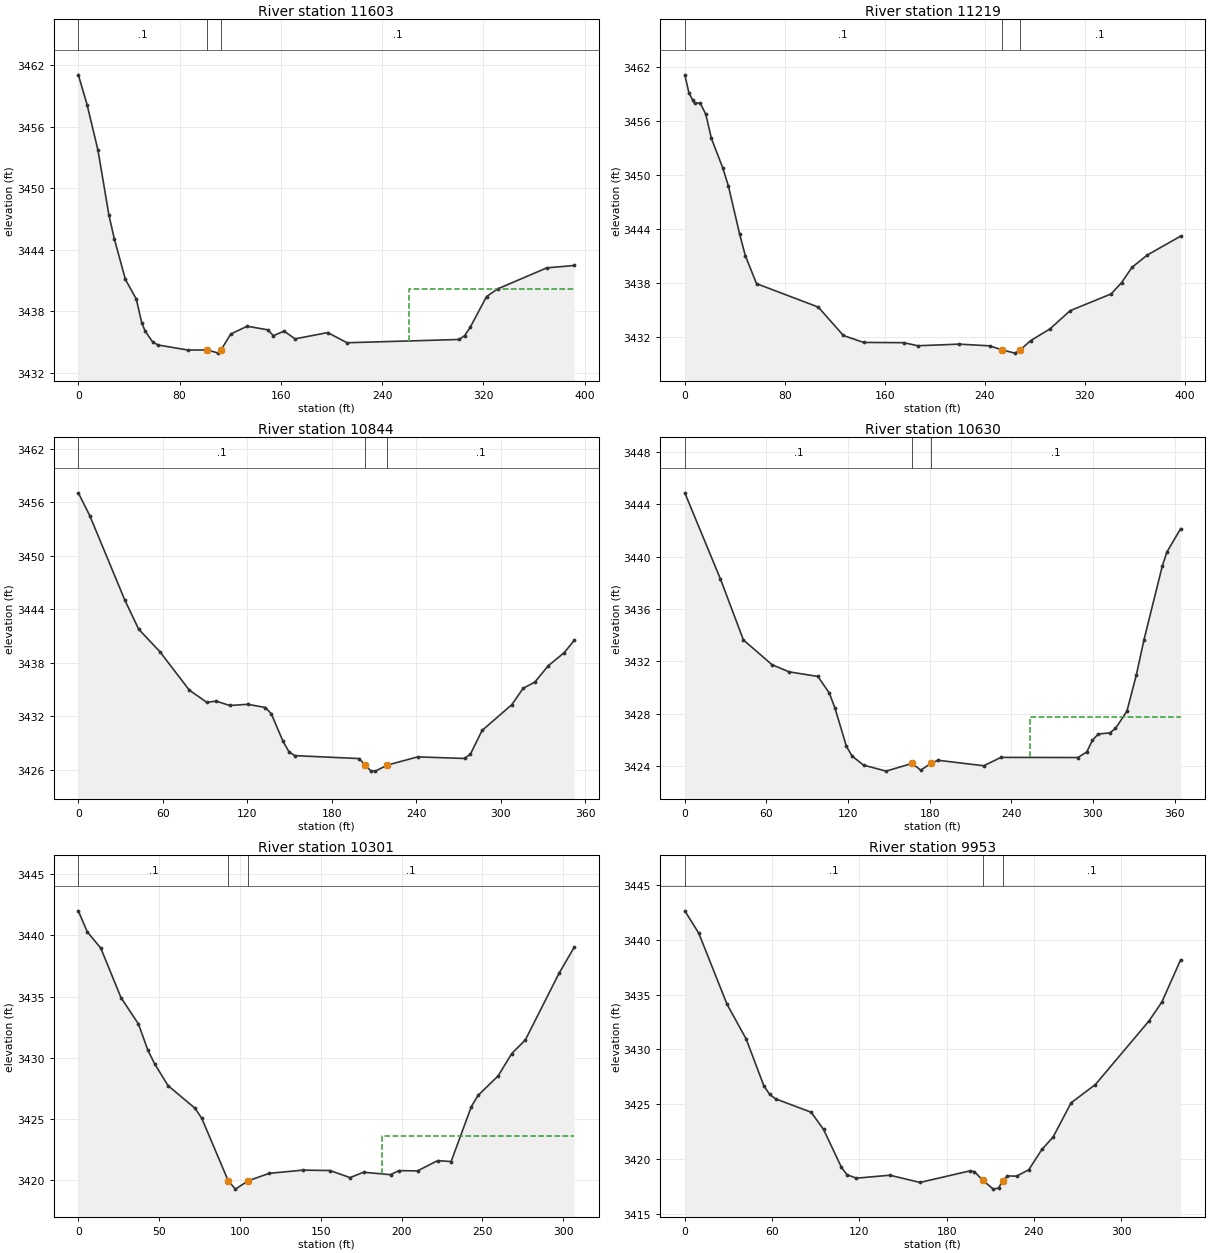
Type RM Length L Ch R = 1 ,11603   ,373,384.3,384.6
XS GIS Cut Line= 2
 2344317.5006327622410.7979487582344466.23673746622773.144416742
#Sta/Elev= 30
       0 3461.03     6.9 3458.13    15.5  3453.7    24.2 3447.36    28.5 3445.03
    37.2 3441.11    45.8  3439.2    50.1 3436.89    52.9 3436.06    58.8 3435.02
    63.1 3434.73    86.6 3434.24     102 3434.25   110.7 3433.94  112.673434.243
   120.4  3435.8   133.4 3436.56   149.6 3436.21   154.1 3435.64   162.6 3436.08
   171.2 3435.33     197 3435.94   212.3 3434.95   300.9 3435.27   305.2 3435.65
   309.6 3436.46   322.5 3439.45   331.2 3440.19   370.1 3442.24   391.7 3442.47
#Mann= 3 ,-1,0
       0      .1       0     102    .045       0  112.67      .1       0
#XS Ineff= 2 , 0
                          260.84         3440.17
Permanent Ineff=
       F       F
Bank Sta=102,112.67
XS Rating Curve= 0 ,0
Exp/Cntr(USF)=0,0
Exp/Cntr=0.3,0.1

Type RM Length L Ch R = 1 ,11219   ,366.9,375.1,369.7
XS GIS Cut Line= 4
2344166.39107946622458.2669183632344214.65119855622550.831409092
2344242.34143082622765.2329218082344262.12016816622838.809824696
#Sta/Elev= 30
       0 3461.18     3.3 3459.19     6.4 3458.34     7.8 3458.03    12.3 3458.04
    16.8  3456.8    21.3 3454.11    30.4 3450.83    34.9 3448.83    43.9 3443.47
    48.4  3441.1    57.4 3437.97   106.8 3435.37   126.9 3432.21   143.1 3431.44
   175.3 3431.41   186.4 3431.07   219.7 3431.25   243.9 3431.06   253.5 3430.63
   264.1 3430.25   268.1 3430.57   276.7 3431.63   292.3 3432.95   308.4 3434.97
   341.2 3436.83   349.5 3438.08   357.9 3439.79   370.2 3441.16   396.8 3443.25
#Mann= 3 ,-1,0
       0      .1       0   253.5    .045       0   268.1      .1       0
Bank Sta=253.5,268.1
XS Rating Curve= 0 ,0
Exp/Cntr(USF)=0,0
Exp/Cntr=0.3,0.1

Type RM Length L Ch R = 1 ,10844   ,212.6,213.7,212.7
XS GIS Cut Line= 2
2343914.80554055622533.4261202372344012.11692824622872.038103419
#Sta/Elev= 30
       0 3457.08     8.1 3454.53      33 3445.05    42.9 3441.77      58 3439.24
    78.8 3434.94    91.3 3433.56    97.9  3433.7   107.6 3433.21   120.5 3433.34
   132.9 3432.98   137.1 3432.28   145.4  3429.2   149.6 3428.03   153.7 3427.58
   199.5 3427.25   203.7 3426.53   207.8 3425.87     211 3425.84   219.6 3426.52
   241.1 3427.44   274.4 3427.26   278.6 3427.75   286.9 3430.41     308  3433.3
     316 3435.13   324.4 3435.84   333.9 3437.67   345.2 3439.13   352.3 3440.51
#Mann= 3 ,-1,0
       0      .1       0   203.7    .045       0   219.6      .1       0
Bank Sta=203.7,219.6
XS Rating Curve= 0 ,0
Exp/Cntr(USF)=0,0
Exp/Cntr=0.3,0.1

Type RM Length L Ch R = 1 ,10630   ,325.5,329.1,326.6
XS GIS Cut Line= 2
2343730.46770858622568.2366979472343843.60208614622914.760176064
#Sta/Elev= 30
       0 3444.89    26.2  3438.3    43.1 3433.64    64.1 3431.75    76.7  3431.2
    97.8 3430.85   106.2 3429.59   110.4 3428.43   118.8 3425.51     123 3424.76
   131.4 3424.07     148 3423.61   167.1  3424.2   173.5 3423.68  180.833424.201
   186.2 3424.44   219.8 3424.02   232.4 3424.66     289 3424.65   295.5 3425.08
   299.7 3425.97     304 3426.45   312.4 3426.53   316.6 3426.87     325 3428.19
     332 3430.99   337.6 3433.67     351 3439.28   354.4 3440.36   364.5 3442.15
#Mann= 3 ,-1,0
       0      .1       0   167.1    .045       0  180.83      .1       0
#XS Ineff= 2 , 0
                          253.48         3427.76
Permanent Ineff=
       F       F
Bank Sta=167.1,180.83
XS Rating Curve= 0 ,0
Exp/Cntr(USF)=0,0
Exp/Cntr=0.3,0.1

Type RM Length L Ch R = 1 ,10301   ,340,347.9,343.1
XS GIS Cut Line= 2
2343507.36355144622671.8772815852343593.59884622622966.184893136
#Sta/Elev= 30
       0    3442     5.5 3440.29    13.9 3438.95    26.4 3434.91    37.2 3432.76
      43 3430.63    47.2 3429.51    55.5 3427.73    72.2 3425.88    76.4 3425.05
   92.733419.954    97.2 3419.28   104.9 3419.95   118.1 3420.57   138.9 3420.83
   155.6  3420.8   168.1 3420.22   176.4 3420.66   193.1 3420.46   198.3 3420.79
   209.8 3420.77   222.3 3421.61   230.6 3421.53   243.1 3426.02   247.3 3426.94
   259.6 3428.51   268.1 3430.35   276.5 3431.46   297.3 3436.89   306.7 3439.02
#Mann= 3 ,-1,0
       0      .1       0   92.73    .045       0   104.9      .1       0
#XS Ineff= 2 , 0
                          187.76         3423.63
Permanent Ineff=
       F       F
Bank Sta=92.73,104.9
XS Rating Curve= 0 ,0
Exp/Cntr(USF)=0,0
Exp/Cntr=0.3,0.1

Type RM Length L Ch R = 1 ,9953    ,383.4,392.4,387
XS GIS Cut Line= 3
2343338.05755985622687.7002714532343353.08940022622770.770968262
2343422.71055564623017.609610208
#Sta/Elev= 30
       0 3442.65     9.6 3440.61      29 3434.13    42.2 3430.95    54.3 3426.69
    58.4 3425.88    62.5 3425.48    86.9 3424.26    95.4 3422.69   107.7 3419.23
   111.6 3418.55     118 3418.24     141 3418.51   161.7 3417.85   195.8  3418.9
   199.1 3418.84     205 3418.03   212.1 3417.24   215.8 3417.35   218.5    3418
   221.8 3418.44   228.2 3418.43   236.5 3419.01   245.5 3420.86   253.2 3421.99
   265.6 3425.12   282.3 3426.79     319 3432.57     328 3434.32   340.9 3438.18
#Mann= 3 ,-1,0
       0      .1       0     205    .045       0   218.5      .1       0
Bank Sta=205,218.5
XS Rating Curve= 0 ,0
Exp/Cntr(USF)=0,0
Exp/Cntr=0.3,0.1

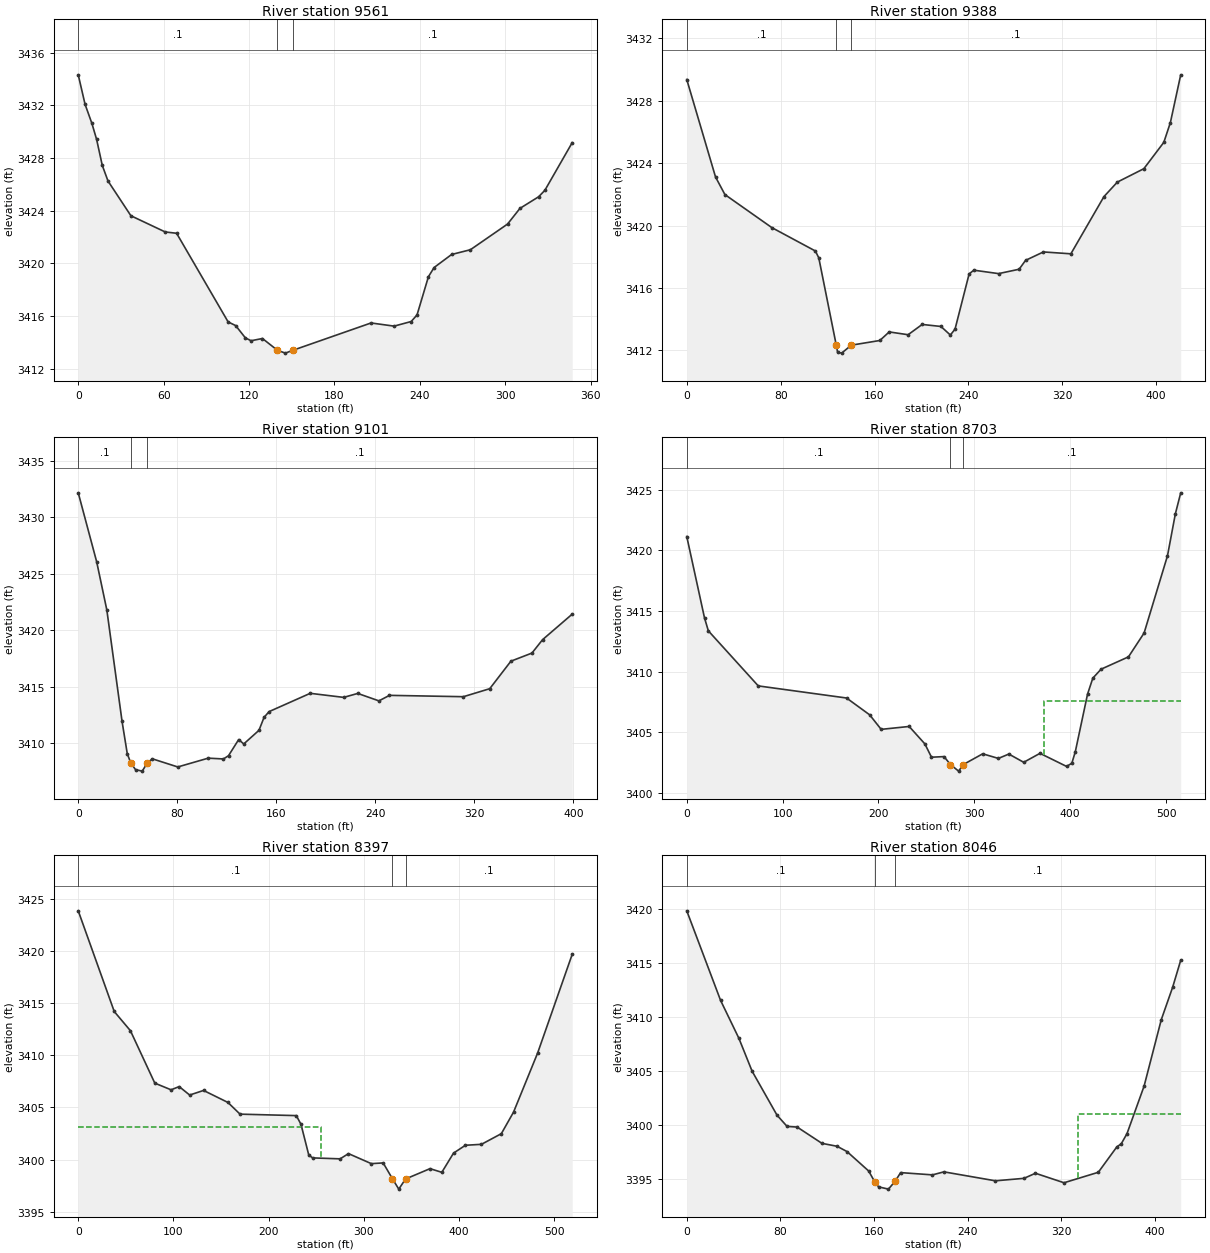
Type RM Length L Ch R = 1 ,9561    ,170.8,173,168.3
XS GIS Cut Line= 3
2343159.98123066622720.3809048552343185.47382544622977.944017711
2343220.63602515623058.817077038
#Sta/Elev= 30
       0 3434.31     4.8 3432.07     9.6 3430.62    12.9 3429.41    16.9 3427.43
    20.9 3426.25      37 3423.61    61.1 3422.38    69.1 3422.28   105.3 3415.55
   110.6 3415.27   117.4 3414.34   121.4 3414.12   129.4 3414.29   139.9  3413.4
   145.5 3413.18   150.9  3413.4   205.7 3415.47   221.9 3415.23   233.9 3415.58
     238 3416.08     246 3418.98     250 3419.68   262.3 3420.67   275.5 3421.03
   301.6 3422.98   310.3 3424.17   323.4 3425.05   327.8 3425.54     347 3429.16
#Mann= 3 ,-1,0
       0      .1       0   139.9    .045       0   150.9      .1       0
Bank Sta=139.9,150.9
XS Rating Curve= 0 ,0
Exp/Cntr(USF)=0,0
Exp/Cntr=0.3,0.1

Type RM Length L Ch R = 1 ,9388    ,287.3,286.7,284.4
XS GIS Cut Line= 3
2343056.25274152622732.6876747522343063.28518146623006.073777477
2343164.37650562623113.318486585
#Sta/Elev= 30
       0 3429.37    24.5 3423.12    32.5 3421.99    72.5 3419.87   109.6 3418.37
   112.5 3417.93  127.443412.313   128.5 3411.88     132 3411.82   140.2 3412.33
   164.5 3412.63   172.5 3413.18   188.6    3413   200.6 3413.66   216.6 3413.53
   224.6 3412.98   228.6 3413.36   240.6  3416.9   244.6 3417.14   265.7 3416.92
   283.2  3417.2   288.7 3417.77   303.9 3418.31   327.3 3418.19   355.5 3421.86
   366.9 3422.79   389.5 3423.65   406.5 3425.34   412.1 3426.61   420.9 3429.67
#Mann= 3 ,-1,0
       0      .1       0  127.44    .045       0   140.2      .1       0
Bank Sta=127.44,140.2
XS Rating Curve= 0 ,0
Exp/Cntr(USF)=0,0
Exp/Cntr=0.3,0.1

Type RM Length L Ch R = 1 ,9101    ,400.7,398.1,392
XS GIS Cut Line= 3
2342767.46118431622834.6558684852342805.30161933623005.778724603
 2342882.9291961 623215.64538618
#Sta/Elev= 30
       0 3432.18    14.9 3426.06    23.1 3421.79    35.4 3411.91    39.6 3409.05
    42.43408.235    46.3 3407.63    51.7  3407.5    55.8 3408.23    59.9 3408.59
    80.4 3407.87     105 3408.65   117.3 3408.58   121.4 3408.87   129.6  3410.3
   133.7 3409.91     146 3411.12   150.1 3412.27   154.2 3412.78   187.4  3414.4
   214.4 3414.04   225.8 3414.39   242.9 3413.73   251.4 3414.22   311.1  3414.1
   332.4 3414.81   349.5 3417.25   366.5 3417.97   375.1 3419.16     399 3421.42
#Mann= 3 ,-1,0
       0      .1       0    42.4    .045       0    55.8      .1       0
Bank Sta=42.4,55.8
XS Rating Curve= 0 ,0
Exp/Cntr(USF)=0,0
Exp/Cntr=0.3,0.1

Type RM Length L Ch R = 1 ,8703    ,298.4,305.4,311.3
XS GIS Cut Line= 4
2342425.54675725622846.7542665072342438.16973262623059.241018585
2342598.06075398623208.612893808 2342614.1901114623290.662233719
#Sta/Elev= 30
       0 3421.15    18.5 3414.43    22.5 3413.36    74.6 3408.81   166.7 3407.81
   190.8 3406.42   202.8 3405.22     232 3405.46   248.4 3404.02   255.3 3402.92
   268.4 3402.97   275.1 3402.31   283.6 3401.77  288.523402.315   308.7  3403.2
   325.1 3402.82     336 3403.18   351.5  3402.5   368.5 3403.24   396.2 3402.16
   401.7 3402.42   405.3 3403.36   418.1 3408.13   423.6 3409.45   432.2 3410.19
   460.8 3411.21   477.1 3413.18   501.5 3419.56   509.7 3423.02   515.3 3424.76
#Mann= 3 ,-1,0
       0      .1       0   275.1    .045       0  288.52      .1       0
#XS Ineff= 2 , 0
                          372.68          3407.6
Permanent Ineff=
       F       F
Bank Sta=275.1,288.52
XS Rating Curve= 0 ,0
Exp/Cntr(USF)=0,0
Exp/Cntr=0.3,0.1

Type RM Length L Ch R = 1 ,8397    ,351.9,351,327.3
XS GIS Cut Line= 4
2342249.13054638622865.7814990912342329.12455071623081.149972299
2342290.44613103623246.4123109242342327.36644073 623359.81040498
#Sta/Elev= 30
       0 3423.82    37.8 3414.18    54.8 3412.34    80.4 3407.32    97.5 3406.68
     106 3406.99     117 3406.18   131.6 3406.62   157.2 3405.47   169.9 3404.35
     229 3404.21   233.9 3403.38   242.1 3400.43   246.2 3400.16     275 3400.07
   283.8 3400.57   307.8 3399.61   320.2 3399.68  329.993398.156   336.6 3397.17
   343.7 3398.14   369.4 3399.13   381.8 3398.78   394.1 3400.62   406.6 3401.37
   423.4 3401.46   444.3 3402.48   457.1 3404.54   482.4  3410.2   518.7 3419.65
#Mann= 3 ,-1,0
       0      .1       0  329.99    .045       0   343.7      .1       0
#XS Ineff= 2 , 0
          254.64 3403.16
Permanent Ineff=
       F       F
Bank Sta=329.99,343.7
XS Rating Curve= 0 ,0
Exp/Cntr(USF)=0,0
Exp/Cntr=0.3,0.1

Type RM Length L Ch R = 1 ,8046    ,411.3,416.6,420.8
XS GIS Cut Line= 4
2341967.23696404623040.9034183552342017.34309862623175.398832235
2342066.57017821623214.0772519142342190.51693218623390.767305444
#Sta/Elev= 30
       0 3419.84    28.9 3411.54    44.5 3408.04    55.8 3404.99    77.1 3400.91
    85.7 3399.87    94.3 3399.81   115.5  3398.3   128.4 3398.03   136.9 3397.54
   155.4 3395.74   160.83394.697   163.9 3394.27   172.3 3394.06   178.1  3394.8
   182.7 3395.59   209.9 3395.38   219.7 3395.66   263.7 3394.83   288.1 3395.06
   297.9 3395.53   322.3 3394.65   351.6 3395.62   367.4 3397.97   371.2 3398.26
   376.1  3399.2   390.7  3403.6   405.4 3409.76   415.1 3412.76     422 3415.26
#Mann= 3 ,-1,0
       0      .1       0   160.8    .045       0   178.1      .1       0
#XS Ineff= 2 , 0
                          334.24         3401.04
Permanent Ineff=
       F       F
Bank Sta=160.8,178.1
XS Rating Curve= 0 ,0
Exp/Cntr(USF)=0,0
Exp/Cntr=0.3,0.1

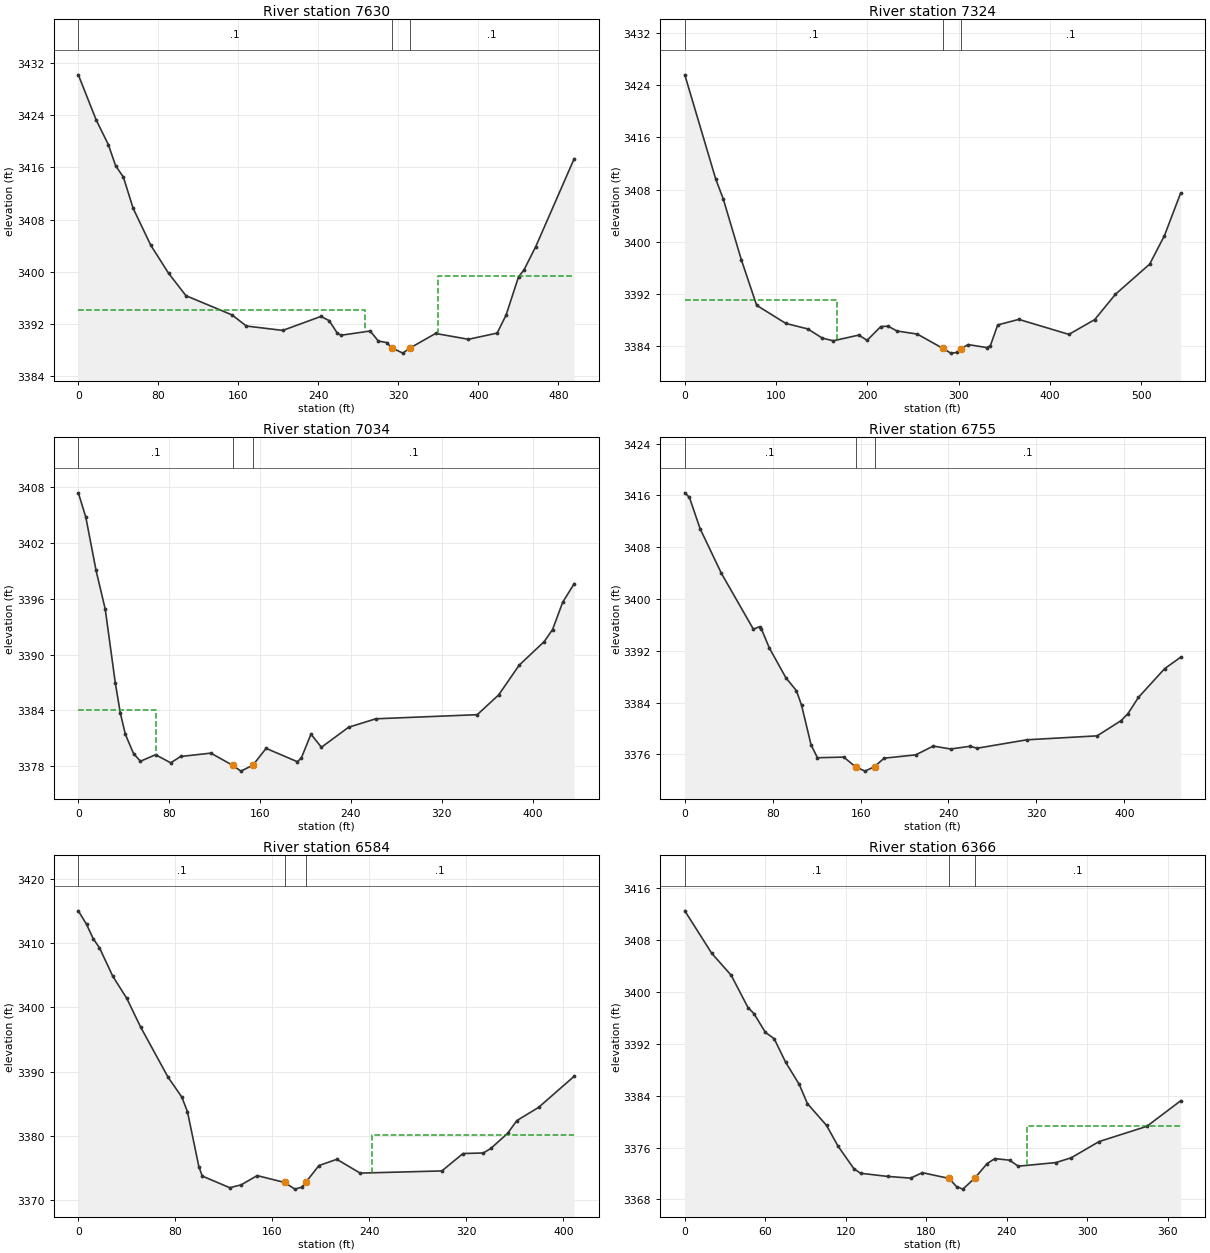
Type RM Length L Ch R = 1 ,7630    ,299.1,306.1,303.7
XS GIS Cut Line= 4
2341766.32877544623099.301362501 2341859.5985379623303.372797664
2341905.18150452623509.5480620562341943.75170704623555.832305083
#Sta/Elev= 30
       0 3430.18    17.9 3423.25      30  3419.5    37.2 3416.29    45.1  3414.5
    54.8 3409.74    72.4 3404.09    90.3 3399.78   107.6 3396.36   153.7 3393.41
     168 3391.71   204.4 3391.04   242.6 3393.18   250.8 3392.54     259 3390.61
   262.8  3390.3   291.8 3390.95     300 3389.41   308.2 3389.18   313.6 3388.35
   324.5 3387.56   331.2  3388.3   357.2 3390.57   390.1 3389.68   418.8 3390.63
   427.7 3393.38   440.2 3399.25   445.5 3400.27   457.3 3403.84   495.8 3417.33
#Mann= 3 ,-1,0
       0      .1       0   313.6    .045       0   331.2      .1       0
#XS Ineff= 2 , 0
          286.32 3394.17  360.09          3399.3
Permanent Ineff=
       F       F
Bank Sta=313.6,331.2
XS Rating Curve= 0 ,0
Exp/Cntr(USF)=0,0
Exp/Cntr=0.3,0.1

Type RM Length L Ch R = 1 ,7324    ,299.4,289.8,279.3
XS GIS Cut Line= 4
2341593.35552183623194.5480663552341617.96906163623267.509630748
2341625.00150157623540.8957334732341764.77124541623673.633037369
#Sta/Elev= 30
       0 3425.59    33.8 3409.66    42.2 3406.54    61.9 3397.28    78.7 3390.28
   110.7  3387.5   134.7 3386.66   150.7 3385.25   162.7 3384.84   190.7 3385.72
   199.7 3384.91   214.7 3387.02   222.7 3387.08   232.5 3386.34   254.7 3385.87
   282.7 3383.68   291.4 3382.95   298.7 3383.05   302.3 3383.62   310.5 3384.26
   330.8  3383.8   334.8  3384.1   342.8 3387.27   365.9 3388.12   420.8 3385.82
   449.1 3388.09   471.8 3391.97   509.3 3396.59   525.5 3400.96   543.2 3407.47
#Mann= 3 ,-1,0
       0      .1       0   282.7    .045       0   302.3      .1       0
#XS Ineff= 2 , 0
          167.21 3391.07
Permanent Ineff=
       F       F
Bank Sta=282.7,302.3
XS Rating Curve= 0 ,0
Exp/Cntr(USF)=0,0
Exp/Cntr=0.3,0.1

Type RM Length L Ch R = 1 ,7034    ,277.9,279.4,280.5
XS GIS Cut Line= 2
 2341258.7145011 623557.911052492341653.31252004623744.466056493
#Sta/Elev= 30
       0 3407.33     6.6 3404.71    15.6 3399.02    23.7 3394.85    32.6 3386.91
      37 3383.71    41.4 3381.45    48.6 3379.38    54.7 3378.56      68 3379.26
    81.3 3378.39    90.1 3379.07   116.7 3379.43  135.813378.126   143.2  3377.5
   153.8 3378.15   165.3 3379.94   192.8 3378.51   196.3  3378.9   204.8 3381.46
     214 3380.06   237.9  3382.2   261.9 3383.11   351.2 3383.55   370.1 3385.68
   388.1 3388.86   410.1 3391.38   417.5 3392.68   426.4  3395.6   436.5 3397.59
#Mann= 3 ,-1,0
       0      .1       0  135.81    .045       0   153.8      .1       0
#XS Ineff= 2 , 0
           68.31 3384.05
Permanent Ineff=
       F       F
Bank Sta=135.81,153.8
XS Rating Curve= 0 ,0
Exp/Cntr(USF)=0,0
Exp/Cntr=0.3,0.1

Type RM Length L Ch R = 1 ,6755    ,168.7,170.8,171.9
XS GIS Cut Line= 2
2341067.27585824 623726.884956642341444.29277733623974.973810131
#Sta/Elev= 30
       0  3416.4     4.2  3415.7    13.9 3410.87    33.3 3403.97    62.4 3395.34
    68.1 3395.72    69.7 3395.39    76.9 3392.45    92.1 3387.81   101.6 3385.84
   106.3 3383.57   114.9 3377.49   120.7 3375.48   144.7 3375.58   155.4 3374.07
     164 3373.41   172.7  3374.1   181.4 3375.41   210.2 3375.92   226.1 3377.28
     242 3376.83   259.6 3377.25   266.1 3376.95   311.3 3378.25   375.3 3378.86
   397.1 3381.21   403.3 3382.28   412.9  3384.8   436.8 3389.25   451.3    3391
#Mann= 3 ,-1,0
       0      .1       0   155.4    .045       0   172.7      .1       0
Bank Sta=155.4,172.7
XS Rating Curve= 0 ,0
Exp/Cntr(USF)=0,0
Exp/Cntr=0.3,0.1

Type RM Length L Ch R = 1 ,6584    ,214.2,217.6,217.1
XS GIS Cut Line= 2
2340983.27727005623825.5344613742341278.24905649624108.785514573
#Sta/Elev= 30
       0 3415.07     6.8 3412.95    12.3 3410.72    17.4 3409.32    28.4 3404.87
      40  3401.4    51.3 3396.97    73.9 3389.15    85.3 3386.03      90 3383.74
    99.4 3375.17   102.2  3373.7   124.9 3371.88   134.3 3372.33   147.5 3373.77
   170.1  3372.7   178.6 3371.66   184.3 3371.97  187.513372.704   198.4 3375.34
   213.2 3376.31   232.4 3374.16   299.8  3374.5   317.2 3377.21     334  3377.3
   340.2 3378.01     354 3380.36   361.7 3382.36   379.5  3384.4   408.9 3389.26
#Mann= 3 ,-1,0
       0      .1       0   170.1    .045       0  187.51      .1       0
#XS Ineff= 2 , 0
                          242.26         3380.13
Permanent Ineff=
       F       F
Bank Sta=170.1,187.51
XS Rating Curve= 0 ,0
Exp/Cntr(USF)=0,0
Exp/Cntr=0.3,0.1

Type RM Length L Ch R = 1 ,6366    ,351.4,357.7,354.5
XS GIS Cut Line= 2
2340863.13975439623933.9512438062341090.71732472624225.016119162
#Sta/Elev= 30
       0 3412.53    20.1 3405.97    34.6 3402.58    47.1  3397.6    51.5 3396.68
    60.1 3393.76    66.6  3392.8    75.2 3389.14    85.3 3385.74    91.4 3382.77
   105.6 3379.42   114.2 3376.22     126 3372.73     131 3372.03   151.2 3371.54
   168.3 3371.28     177 3372.12   196.8 3371.24   202.5 3369.98   207.2 3369.58
     216 3371.26   225.3 3373.52     231 3374.29     242 3374.05   248.5 3373.12
   276.6 3373.68     288 3374.42   308.7 3376.92   344.3 3379.27   369.5 3383.21
#Mann= 3 ,-1,0
       0      .1       0   196.8    .045       0     216      .1       0
#XS Ineff= 2 , 0
                          255.01         3379.36
Permanent Ineff=
       F       F
Bank Sta=196.8,216
XS Rating Curve= 0 ,0
Exp/Cntr(USF)=0,0
Exp/Cntr=0.3,0.1