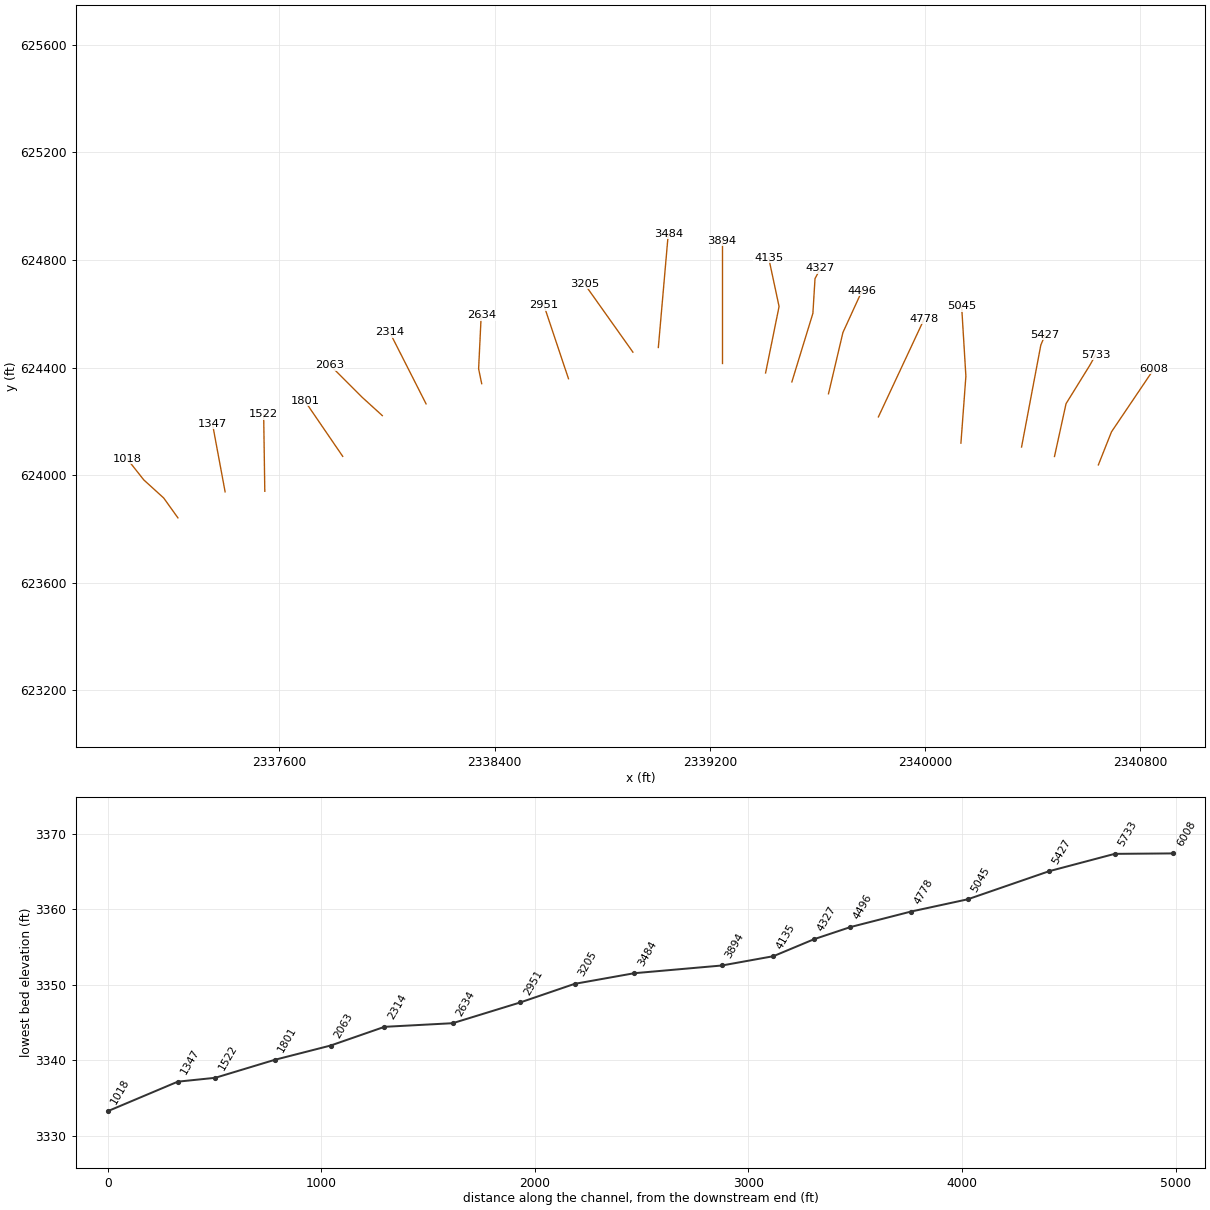
HEC-RAS study ELKRN.prj: ELKRN

--- ELKRN.g01 (geometry) --- (continued)

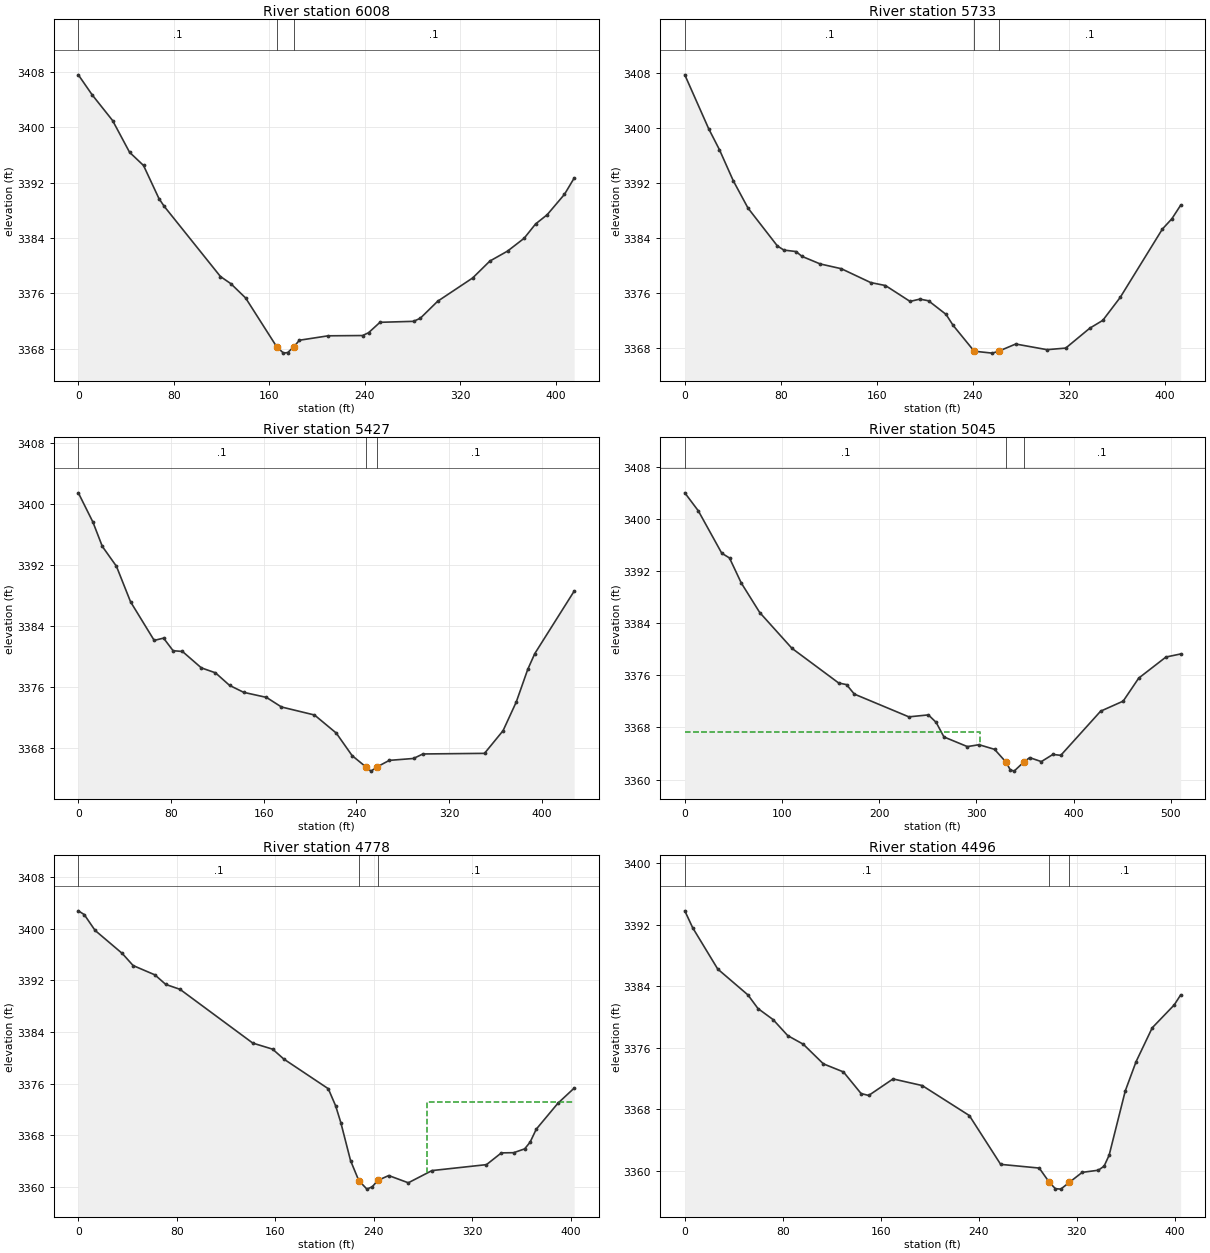
Type RM Length L Ch R = 1 ,6008    ,272.6,275.2,271.5
XS GIS Cut Line= 3
2340644.35273399624038.4611151582340693.18912247624161.528814134
2340851.41902115624395.943478851
#Sta/Elev= 30
       0 3407.56    11.5 3404.69    28.7 3400.96    42.9 3396.38    54.6 3394.47
    67.5  3389.7    71.8  3388.6     119 3378.44   127.7 3377.41   140.1 3375.34
     166 3368.33   171.8 3367.38   175.4 3367.47   180.6 3368.32   185.1 3369.24
   209.2 3369.88     238 3369.92     243 3370.32   252.6 3371.83   280.7 3371.97
   286.4 3372.42   300.9 3374.87   330.2 3378.23   344.6 3380.67   359.4 3382.11
   373.3 3383.96   382.9 3386.03   392.6 3387.36   407.1 3390.31   415.2 3392.65
#Mann= 3 ,-1,0
       0      .1       0     166    .045       0   180.6      .1       0
Bank Sta=166,180.6
XS Rating Curve= 0 ,0
Exp/Cntr(USF)=0,0
Exp/Cntr=0.3,0.1

Type RM Length L Ch R = 1 ,5733    ,301.3,306.6,303.2
XS GIS Cut Line= 4
2340481.23919645624069.7164037872340524.21521832624266.038685487
2340612.40770028624408.5417393512340634.59607511 624447.55179568
#Sta/Elev= 30
       0 3407.67    19.9 3399.86    28.9 3396.81    40.4 3392.32    52.7 3388.35
    77.2 3382.86    82.6 3382.26    92.7 3382.05    97.7 3381.35   112.9 3380.25
   130.5 3379.56     155 3377.55   167.3 3377.12   187.8 3374.82     196 3375.15
   203.2 3374.91   217.8 3372.94   223.7 3371.35   241.33367.597   256.4 3367.32
   261.7  3367.6   275.9 3368.64     302 3367.82   317.6 3368.05   337.7 3370.94
   348.5 3372.07     363 3375.39   398.2 3385.31   406.1  3386.8   413.4 3388.76
#Mann= 3 ,-1,0
       0      .1       0   241.3    .045       0   261.7      .1       0
Bank Sta=241.3,261.7
XS Rating Curve= 0 ,0
Exp/Cntr(USF)=0,0
Exp/Cntr=0.3,0.1

Type RM Length L Ch R = 1 ,5427    ,375,381.7,381.1
XS GIS Cut Line= 3
2340358.84598329624104.8405677862340430.41825364624483.719173544
 2340446.8912365624522.913512071
#Sta/Elev= 30
       0 3401.52    12.6 3397.68    20.7  3394.5    32.9 3391.89    45.1 3387.23
    65.5 3382.17    73.6 3382.47    81.8 3380.82    89.9 3380.72   106.2 3378.57
   118.4 3377.92   130.6 3376.27   142.8 3375.36   162.4  3374.7   175.4 3373.44
   203.9 3372.39   222.7 3370.02   236.4 3367.06     248 3365.62   252.7 3365.03
   258.2 3365.61   268.5 3366.44   289.4 3366.69   297.5 3367.28   350.7 3367.36
   366.7 3370.33   378.1 3374.09     388 3378.36   394.1 3380.44   428.1 3388.63
#Mann= 3 ,-1,0
       0      .1       0     248    .045       0   258.2      .1       0
Bank Sta=248,258.2
XS Rating Curve= 0 ,0
Exp/Cntr(USF)=0,0
Exp/Cntr=0.3,0.1

Type RM Length L Ch R = 1 ,5045    ,268,266.9,260
XS GIS Cut Line= 3
2340133.46059213624119.2683969662340151.92074698624368.040959896
2340136.09775711624628.241237731
#Sta/Elev= 30
       0 3403.97    13.9 3401.21      38 3394.72      46 3393.98    58.1 3390.15
    77.1 3385.62   110.2 3380.14   158.3 3374.82   166.4 3374.57   174.4 3373.12
   230.5 3369.63   250.6 3369.93   258.6 3368.78   266.6 3366.55   290.7 3365.07
   302.7 3365.36   318.7 3364.65   330.7 3362.65   334.8 3361.51   338.8 3361.31
   348.5 3362.67   354.8 3363.38   366.8 3362.77   378.7 3363.87   386.8 3363.73
   427.8  3370.5     451 3372.04     467 3375.57     495  3378.8   510.1 3379.27
#Mann= 3 ,-1,0
       0      .1       0   330.7    .045       0   348.5      .1       0
#XS Ineff= 2 , 0
           303.9 3367.35
Permanent Ineff=
       F       F
Bank Sta=330.7,348.5
XS Rating Curve= 0 ,0
Exp/Cntr(USF)=0,0
Exp/Cntr=0.3,0.1

Type RM Length L Ch R = 1 ,4778    ,281.9,282.1,281.5
XS GIS Cut Line= 2
2339826.67039969624216.8435011542339997.20706827624581.651323119
#Sta/Elev= 30
       0 3402.75     4.8 3402.17    13.6 3399.72    35.7 3396.15    44.5 3394.28
    62.2 3392.84      71 3391.36    82.6  3390.6   141.7 3382.28   157.8 3381.34
   166.9 3379.81     203 3375.22     209 3372.56   213.2 3369.97   221.1 3364.09
  227.783361.007   234.4 3359.68   238.8 3360.06   243.2 3361.03   252.1 3361.78
     268 3360.66   287.2 3362.55   331.5 3363.47   343.6 3365.29   353.6 3365.32
   362.5 3365.91   366.9 3366.94   371.9 3368.95   389.5 3372.97   402.7 3375.31
#Mann= 3 ,-1,0
       0      .1       0  227.78    .045       0   243.2      .1       0
#XS Ineff= 2 , 0
                          283.49         3373.22
Permanent Ineff=
       F       F
Bank Sta=227.78,243.2
XS Rating Curve= 0 ,0
Exp/Cntr(USF)=0,0
Exp/Cntr=0.3,0.1

Type RM Length L Ch R = 1 ,4496    ,165.6,168.9,169.9
XS GIS Cut Line= 3
2339641.18979623624302.9908904372339694.81215078624530.666133543
2339766.01560519624686.258867248
#Sta/Elev= 30
       0 3393.83     6.4 3391.64    26.9 3386.26    51.6 3382.89    59.8 3381.12
    72.1 3379.69    84.1  3377.6    96.8 3376.48   113.2 3373.93   129.6 3372.88
     144 3370.07   150.2 3369.82   170.1 3371.97   193.9 3371.11   232.4 3367.21
     258 3360.86   289.5 3360.38  297.83 3358.51   302.7  3357.7   307.1 3357.64
   314.1 3358.52   324.6 3359.82   337.8  3360.1   342.5 3360.63   346.6 3362.05
   359.8 3370.42   368.6 3374.21   381.8 3378.62   399.8  3381.6     405 3382.89
#Mann= 3 ,-1,0
       0      .1       0  297.83    .045       0   314.1      .1       0
Bank Sta=297.83,314.1
XS Rating Curve= 0 ,0
Exp/Cntr(USF)=0,0
Exp/Cntr=0.3,0.1

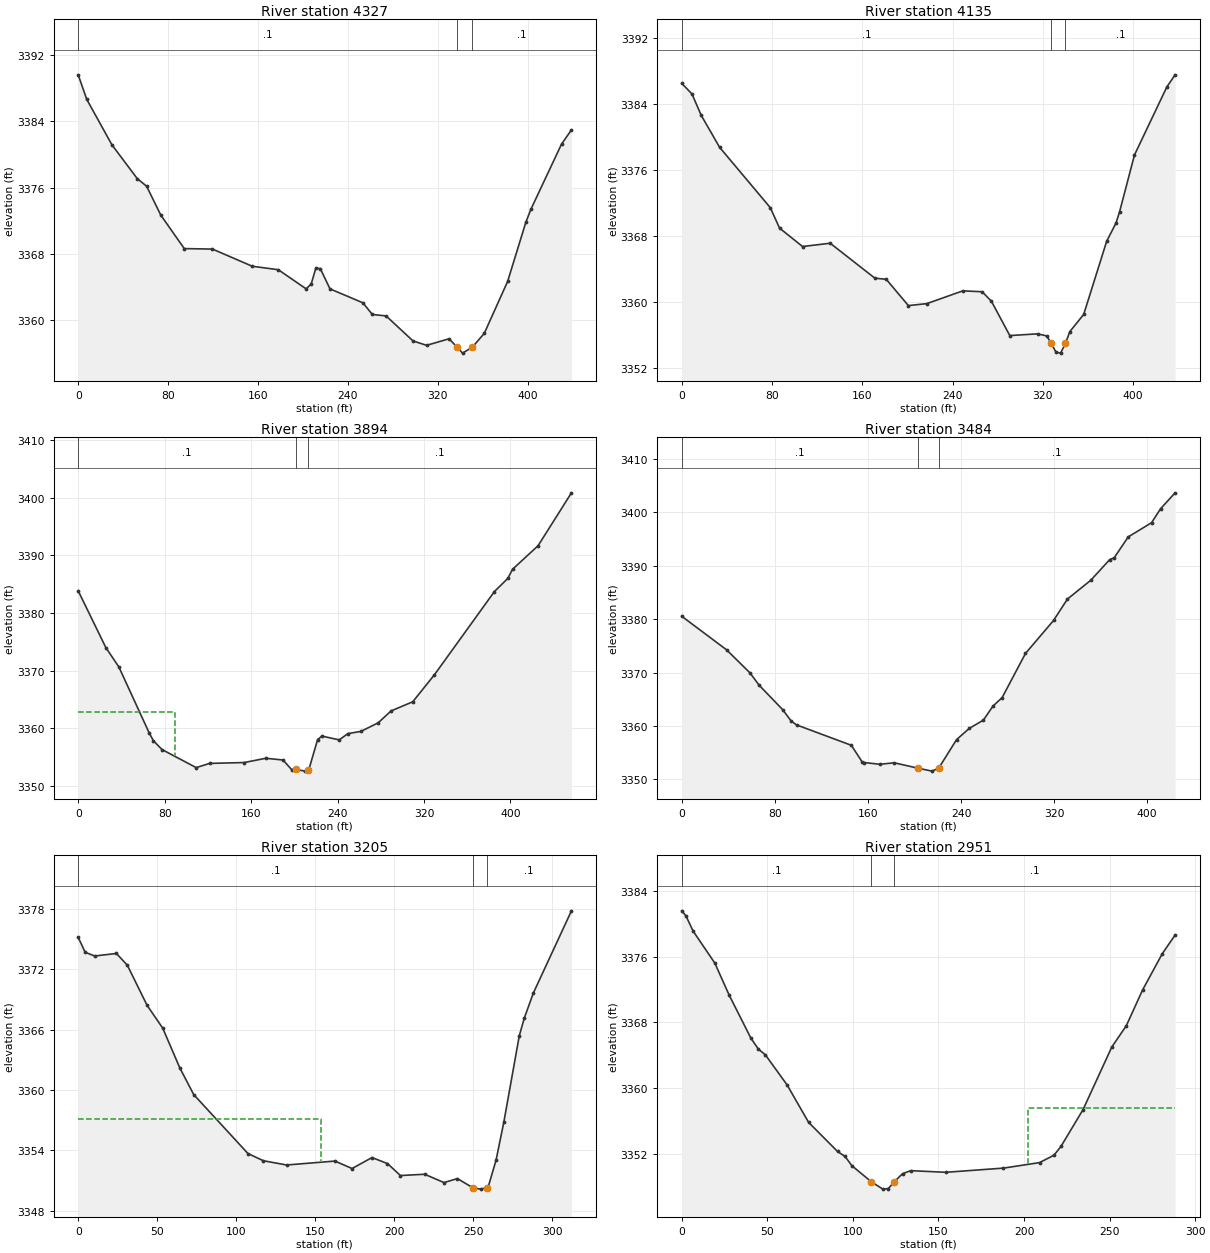
Type RM Length L Ch R = 1 ,4327    ,186.3,191.6,190.4
XS GIS Cut Line= 4
2339504.93627236624346.9436400712339583.17216671 624601.86958795
2339591.08366165624731.0906718752339611.30192648624768.890036561
#Sta/Elev= 30
       0 3389.62     7.6 3386.66      30 3381.18    52.5 3377.11    60.9 3376.18
    73.5  3372.7    94.4 3368.66   119.5  3368.6   154.9 3366.53   178.1 3366.11
   202.9  3363.8   207.4  3364.4   211.5 3366.31   215.5 3366.24   224.1  3363.8
   253.4 3362.12   261.8 3360.71     274 3360.54     298 3357.52   310.1 3356.99
   330.1 3357.78   337.4 3356.74   342.1 3356.05  350.713356.758   361.4 3358.43
   382.2  3364.7   398.4 3371.83     403 3373.43   430.2 3381.27     439 3382.98
#Mann= 3 ,-1,0
       0      .1       0   337.4    .045       0  350.71      .1       0
Bank Sta=337.4,350.71
XS Rating Curve= 0 ,0
Exp/Cntr(USF)=0,0
Exp/Cntr=0.3,0.1

Type RM Length L Ch R = 1 ,4135    ,239.1,241.1,237.5
XS GIS Cut Line= 3
2339407.36116817624380.3477297932339457.46730276624627.362182738
2339418.78888308624808.447511232
#Sta/Elev= 30
       0 3386.53       9 3385.24    17.2 3382.65    33.5 3378.77    78.4 3371.45
    86.6 3368.97     107 3366.73   131.5 3367.13   171.1 3362.89   181.2 3362.75
   200.8 3359.56   217.2  3359.8   249.1 3361.35   266.2 3361.24   274.4 3360.09
   290.7 3355.92   315.3 3356.13   323.4 3355.88   327.5 3354.98   331.6 3353.91
   335.7 3353.79  340.033354.969   343.9  3356.4   356.2 3358.49   376.6 3367.38
   384.8 3369.57     388 3370.94   401.2 3377.84   429.9  3386.1   437.2 3387.57
#Mann= 3 ,-1,0
       0      .1       0   327.5    .045       0  340.03      .1       0
Bank Sta=327.5,340.03
XS Rating Curve= 0 ,0
Exp/Cntr(USF)=0,0
Exp/Cntr=0.3,0.1

Type RM Length L Ch R = 1 ,3894    ,406.3,410.2,405.9
XS GIS Cut Line= 2
 2339243.7954539624415.555106541 2339243.7954539624872.100986315
#Sta/Elev= 30
       0 3383.84    25.6 3373.99    37.6 3370.65    65.6 3359.23    69.6 3357.83
    77.6  3356.3   109.2 3353.17   121.6  3353.9   153.6 3354.05   173.6 3354.79
   189.6 3354.49   197.6  3352.8   201.83352.875   209.6 3352.56   212.73352.835
   213.6 3352.92   221.6 3358.04   225.6 3358.64   241.6 3357.98   249.6 3359.07
   261.6 3359.45   277.6 3360.94   289.6 3363.01   309.6 3364.59   329.6 3369.26
   385.2 3383.72   397.6    3386     402 3387.59   425.6 3391.67   456.5 3400.85
#Mann= 3 ,-1,0
       0      .1       0   201.8    .045       0   212.7      .1       0
#XS Ineff= 2 , 0
           89.25  3362.8
Permanent Ineff=
       F       F
Bank Sta=201.8,212.7
XS Rating Curve= 0 ,0
Exp/Cntr(USF)=0,0
Exp/Cntr=0.3,0.1

Type RM Length L Ch R = 1 ,3484    ,273.2,279.7,281.3
XS GIS Cut Line= 2
2339008.66364555624474.9154594252339045.53544691624897.330798975
#Sta/Elev= 30
       0 3380.53    38.4 3374.27    58.5 3369.96    66.5 3367.62    86.6 3363.07
      94 3360.92    98.6  3360.2   145.7 3356.38   154.9  3353.3   156.7 3353.15
   170.2 3352.82   182.6  3353.1     203 3352.09   215.1 3351.54   220.83352.098
   236.2 3357.45   247.2 3359.56   259.2 3361.09   267.5 3363.73   275.3  3365.3
   295.4 3373.58   319.5 3379.75   331.5 3383.77   351.6  3387.3   367.7 3391.13
   371.7 3391.51   383.7  3395.4   403.8 3398.07   411.5 3400.67     424 3403.66
#Mann= 3 ,-1,0
       0      .1       0     203    .045       0   220.8      .1       0
Bank Sta=203,220.8
XS Rating Curve= 0 ,0
Exp/Cntr(USF)=0,0
Exp/Cntr=0.3,0.1

Type RM Length L Ch R = 1 ,3205    ,257.7,253.7,251.4
XS GIS Cut Line= 2
2338914.19719645624457.5923410892338733.56241889624712.071524567
#Sta/Elev= 30
       0 3375.16     4.4 3373.68    10.4 3373.31    24.2 3373.56    31.1 3372.39
    43.6  3368.4    53.5 3366.13    64.3 3362.18    73.1 3359.53   107.4 3353.67
   117.2 3352.95   131.9 3352.53   162.4 3352.92   173.3 3352.18   185.9 3353.27
   195.7 3352.67   203.9 3351.48   219.2 3351.61   231.5 3350.78   239.9 3351.18
   249.7 3350.27   254.6 3350.13  258.363350.278   259.5 3350.39   264.4 3353.01
   269.3 3356.78   279.1 3365.38   282.3 3367.15     288 3369.63   312.1  3377.8
#Mann= 3 ,-1,0
       0      .1       0   249.7    .045       0  258.36      .1       0
#XS Ineff= 2 , 0
          153.64 3357.12
Permanent Ineff=
       F       F
Bank Sta=249.7,258.36
XS Rating Curve= 0 ,0
Exp/Cntr(USF)=0,0
Exp/Cntr=0.3,0.1

Type RM Length L Ch R = 1 ,2951    ,317.8,316.9,313.9
XS GIS Cut Line= 2
2338674.62274833 624358.880200392338583.20102909624632.266303116
#Sta/Elev= 30
       0 3381.57     2.4 3380.96     6.6  3379.1    19.3  3375.2    27.7 3371.29
    40.4 3366.05    44.8 3364.72    48.8 3364.04    61.5 3360.38    74.1 3355.81
      91 3352.27    95.4 3351.66    99.4 3350.53  110.68 3348.59   117.5 3347.68
   120.7 3347.75  124.283348.599     129 3349.56   133.8 3349.93   154.3 3349.73
     188 3350.24   209.1 3350.91   217.5 3351.81   221.6 3352.88   234.5 3357.36
   251.3 3364.98   259.8 3367.58   269.3 3371.93   280.8 3376.34   288.3 3378.62
#Mann= 3 ,-1,0
       0      .1       0  110.68    .045       0  124.28      .1       0
#XS Ineff= 1 ,-1
   202.6288.2671 3357.51
Permanent Ineff=
       F
Bank Sta=110.68,124.28
XS Rating Curve= 0 ,0
Exp/Cntr(USF)=0,0
Exp/Cntr=0.3,0.1

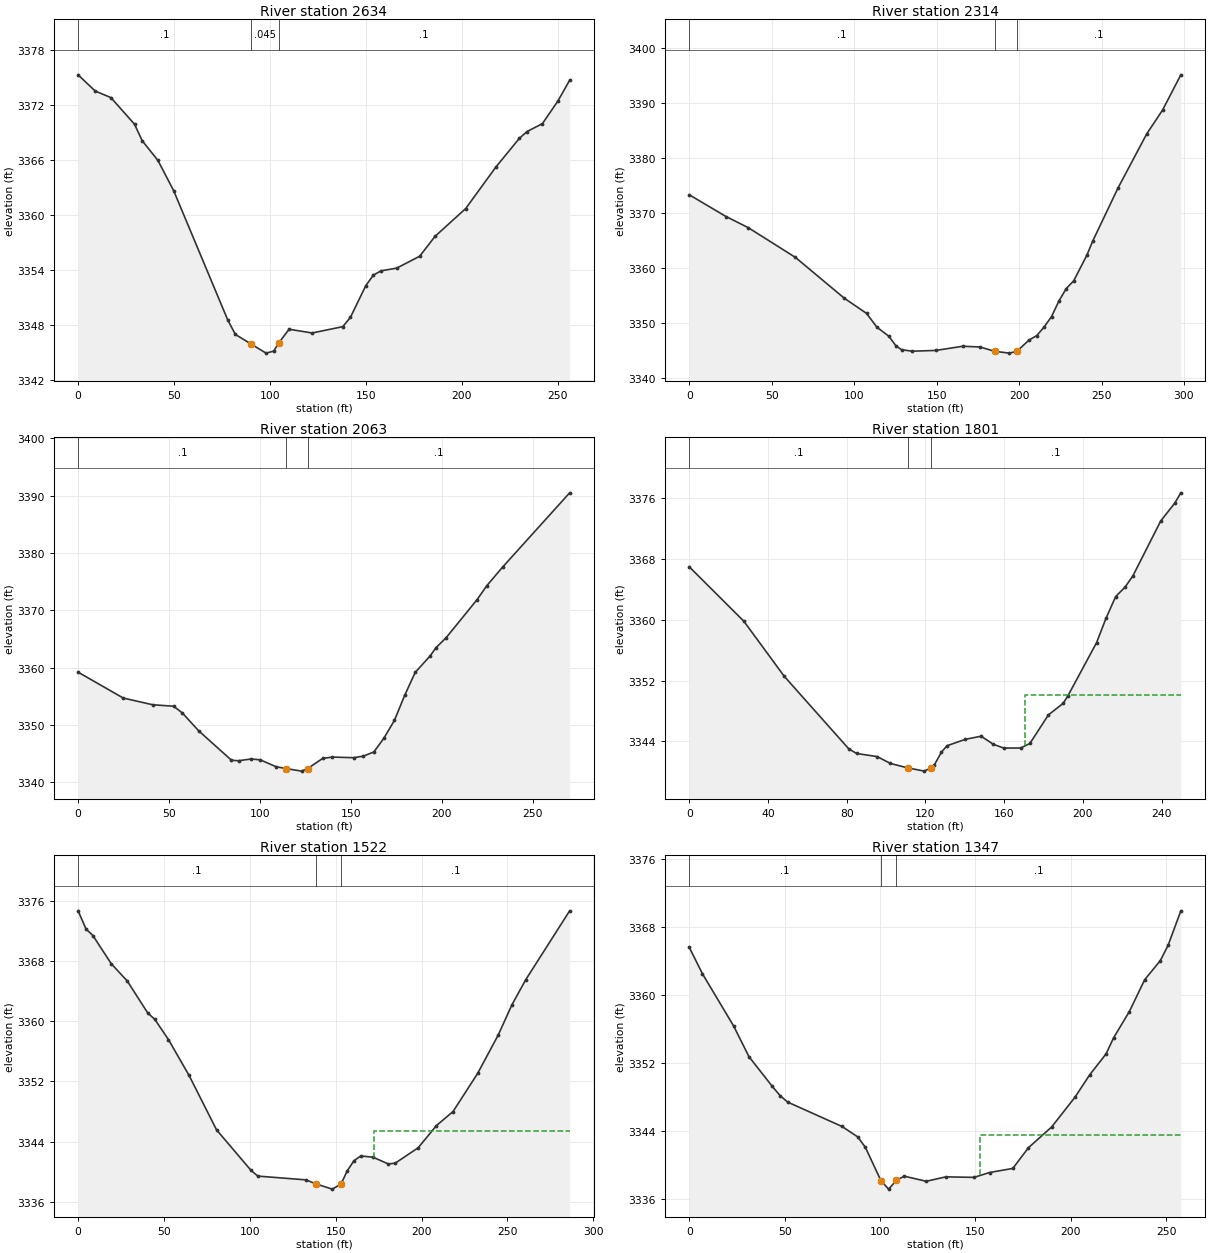
Type RM Length L Ch R = 1 ,2634    ,311.2,319.4,320.2
XS GIS Cut Line= 3
2338352.00956601624340.4200455442338340.58185111624395.800510083
2338350.25145603624595.345993423
#Sta/Elev= 30
       0 3375.32     8.9 3373.55    17.1 3372.83    29.4 3369.93    33.4 3368.13
    41.6 3365.98    49.8 3362.68      78 3348.56      82 3346.97      90 3345.95
      98 3344.93     102 3345.15  104.493346.003     110 3347.54     122 3347.13
     138 3347.82     142 3348.84     150  3352.3     154 3353.46     158 3353.92
   166.1 3354.21   178.1 3355.51   186.1 3357.68   202.1 3360.72   217.9 3365.27
   230.1 3368.39   234.1 3369.13   242.1 3369.99   250.2 3372.47   256.3 3374.73
#Mann= 3 ,-1,0
       0      .1       0      90    .045       0  104.49      .1       0
Bank Sta=90,104.49
XS Rating Curve= 0 ,0
Exp/Cntr(USF)=0,0
Exp/Cntr=0.3,0.1

Type RM Length L Ch R = 1 ,2314    ,246.3,251.7,251.5
XS GIS Cut Line= 2
2338145.32314901624265.3250328632338010.36412153624531.090502371
#Sta/Elev= 30
       0 3373.26    22.3  3369.3    35.7 3367.29    64.4 3361.86      94 3354.44
   107.5 3351.68   113.8 3349.16     121 3347.53   125.4 3345.75   128.7 3345.08
   135.1  3344.8   149.5 3344.94   165.8  3345.7   176.3 3345.57   185.2 3344.78
   194.1 3344.45  198.673344.783     206 3346.82   210.7 3347.64   215.2 3349.21
   219.7 3351.11   224.1  3353.9   228.6  3356.2   233.1  3357.6   241.1 3362.26
   244.7 3364.87     260  3374.5   277.4 3384.34     287 3388.67   298.1 3395.09
#Mann= 3 ,-1,0
       0      .1       0   185.2    .045       0  198.67      .1       0
Bank Sta=185.2,198.67
XS Rating Curve= 0 ,0
Exp/Cntr(USF)=0,0
Exp/Cntr=0.3,0.1

Type RM Length L Ch R = 1 ,2063    ,260.7,261.8,258
XS GIS Cut Line= 3
2337982.54845945624221.8305642662337907.34042119624290.201508142
2337788.17963329624409.362296039
#Sta/Elev= 30
       0 3359.23    24.8 3354.72      41 3353.55    52.5 3353.29    57.3 3352.12
    66.3    3349    84.3 3343.88    88.2 3343.79    95.1  3344.1   100.1 3343.95
   108.8 3342.75   114.5 3342.42   122.8 3341.98  126.123342.412   134.4 3344.19
   139.8 3344.43   151.4 3344.32   156.8 3344.59   162.6 3345.33   168.1 3347.73
   173.9 3350.84   179.5 3355.18   185.3 3359.19   193.7 3362.13   196.6 3363.46
   202.2  3365.2   219.3 3371.87   224.6 3374.28   233.3 3377.53   270.2 3390.49
#Mann= 3 ,-1,0
       0      .1       0   114.5    .045       0  126.12      .1       0
Bank Sta=114.5,126.12
XS Rating Curve= 0 ,0
Exp/Cntr(USF)=0,0
Exp/Cntr=0.3,0.1

Type RM Length L Ch R = 1 ,1801    ,280,278.8,272.7
XS GIS Cut Line= 2
2337835.37971676624070.3046119362337694.42315845624276.479876322
#Sta/Elev= 30
       0 3366.94    27.7  3359.8    48.2 3352.57      81 3343.03      85 3342.41
    95.5    3342   102.2  3341.1   110.9 3340.52   119.5 3340.09  122.653340.514
   124.6 3340.94   128.1 3342.57     131 3343.43   140.3 3344.27   148.3 3344.68
   154.5 3343.62   159.8 3343.12   168.4 3343.13   173.1 3343.73   182.5 3347.48
     190    3349   192.5 3350.03     207 3356.99   211.8  3360.2   216.7 3363.04
   221.5 3364.29   225.4 3365.74   239.6 3372.98   246.7 3375.31   249.8 3376.67
#Mann= 3 ,-1,0
       0      .1       0   110.9    .045       0  122.65      .1       0
#XS Ineff= 1 ,-1
  170.46249.75393350.063
Permanent Ineff=
       F
Bank Sta=110.9,122.65
XS Rating Curve= 0 ,0
Exp/Cntr(USF)=0,0
Exp/Cntr=0.3,0.1

Type RM Length L Ch R = 1 ,1522    ,173.2,175.4,176.3
XS GIS Cut Line= 2
2337545.75255964623940.5684761822337541.54490119624226.689251249
#Sta/Elev= 30
       0 3374.65     4.6 3372.24     8.6 3371.37    19.3 3367.63    28.6 3365.34
    40.6 3361.07    44.6 3360.26    52.6 3357.56    64.6  3352.8    80.6 3345.58
   100.6 3340.22   104.6 3339.44   132.6 3338.94  138.633338.393     148 3337.71
  153.143338.391   156.6  3340.1   160.6 3341.48   164.6 3342.11   171.7 3341.95
   180.6 3341.05   184.6 3341.15     198  3343.2   208.6 3346.14   218.3 3348.01
   232.6 3353.06   244.6 3358.16   252.6 3362.18   260.6  3365.5   286.2 3374.65
#Mann= 3 ,-1,0
       0      .1       0  138.63    .045       0  153.14      .1       0
#XS Ineff= 1 ,-1
  172.47286.1517 3345.45
Permanent Ineff=
       F
Bank Sta=138.63,153.14
XS Rating Curve= 0 ,0
Exp/Cntr(USF)=0,0
Exp/Cntr=0.3,0.1

Type RM Length L Ch R = 1 ,1347    ,325,328.4,329.1
XS GIS Cut Line= 2
2337398.25333979 623938.406637522337351.10652678624191.749753215
#Sta/Elev= 30
       0 3365.57     6.9 3362.47    23.2 3356.36    31.3 3352.74    43.5 3349.26
    47.6 3348.17    51.6 3347.41    80.1 3344.55    88.3 3343.33    92.3 3342.11
  100.433338.208   104.5  3337.2   108.6 3338.24   112.7 3338.72   124.2 3338.12
   134.5 3338.64   149.3 3338.58   157.4 3339.15   169.6 3339.63   177.8 3342.06
     190  3344.5   202.2 3347.99     210 3350.64   218.5 3353.07   222.5 3354.98
   230.7 3358.04   238.8  3361.8   246.9    3364     251  3365.8   257.7 3369.86
#Mann= 3 ,-1,0
       0      .1       0  100.43    .045       0   108.6      .1       0
#XS Ineff= 2 , 0
                          152.46         3343.57
Permanent Ineff=
       F       F
Bank Sta=100.43,108.6
XS Rating Curve= 0 ,0
Exp/Cntr(USF)=0,0
Exp/Cntr=0.3,0.1

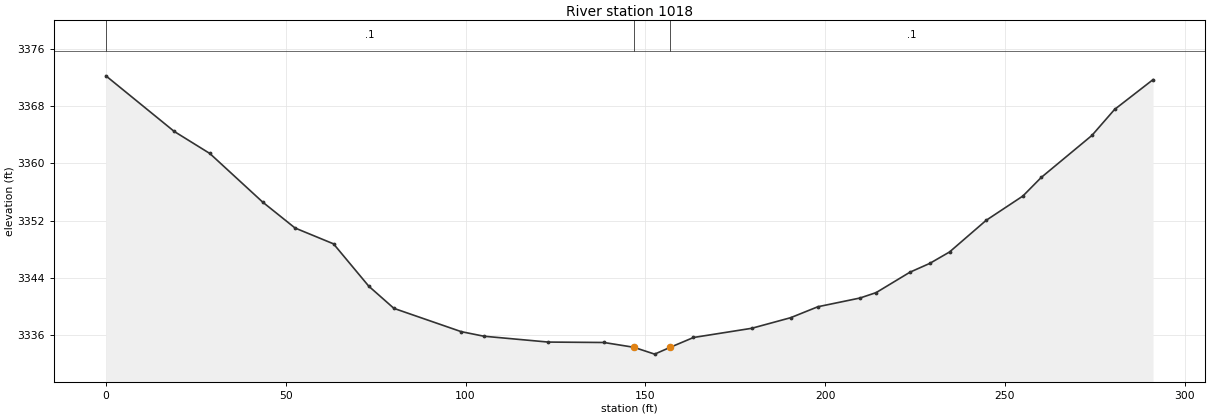
Type RM Length L Ch R = 1 ,1018    ,211.1,212.6,208.2
XS GIS Cut Line= 4
2337222.75544823623841.7132482772337169.92829631623915.557654195
2337096.08389039623982.585653413 2337033.6001623624061.542364356
#Sta/Elev= 30
       0 3372.28      19 3364.49    28.9  3361.4    43.6 3354.59    52.6 3350.96
    63.3 3348.74    73.1 3342.81    80.1  3339.7    98.8 3336.44   105.1  3335.8
     123 3334.98   138.5 3334.92   146.8 3334.25   152.6 3333.29  156.893334.236
   163.4 3335.62   179.6 3336.91   190.4 3338.39     198 3339.93   209.7 3341.15
   214.2 3341.91   223.6 3344.77   229.1    3346   234.6  3347.6   244.8 3352.04
     255 3355.44   260.1 3358.04   274.2 3363.93   280.5 3367.57   291.2 3371.75
#Mann= 3 ,-1,0
       0      .1       0   146.8    .045       0  156.89      .1       0
Bank Sta=146.8,156.89
XS Rating Curve= 0 ,0
Exp/Cntr(USF)=0,0
Exp/Cntr=0.3,0.1