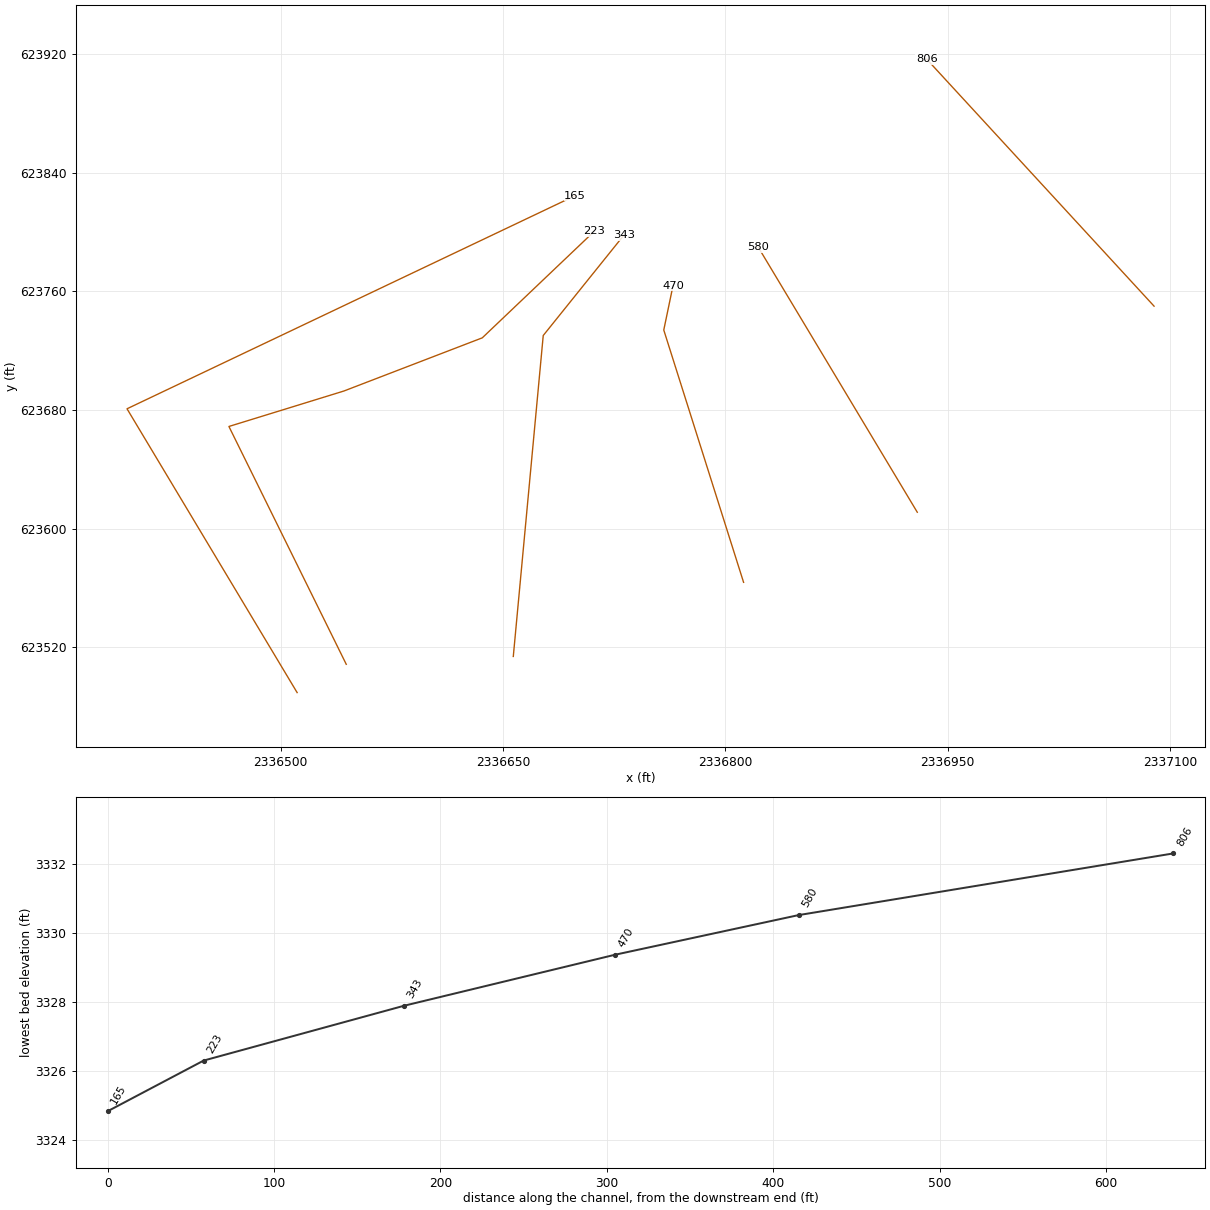
HEC-RAS study ELKRN.prj: ELKRN

--- ELKRN.g01 (geometry) --- (continued)

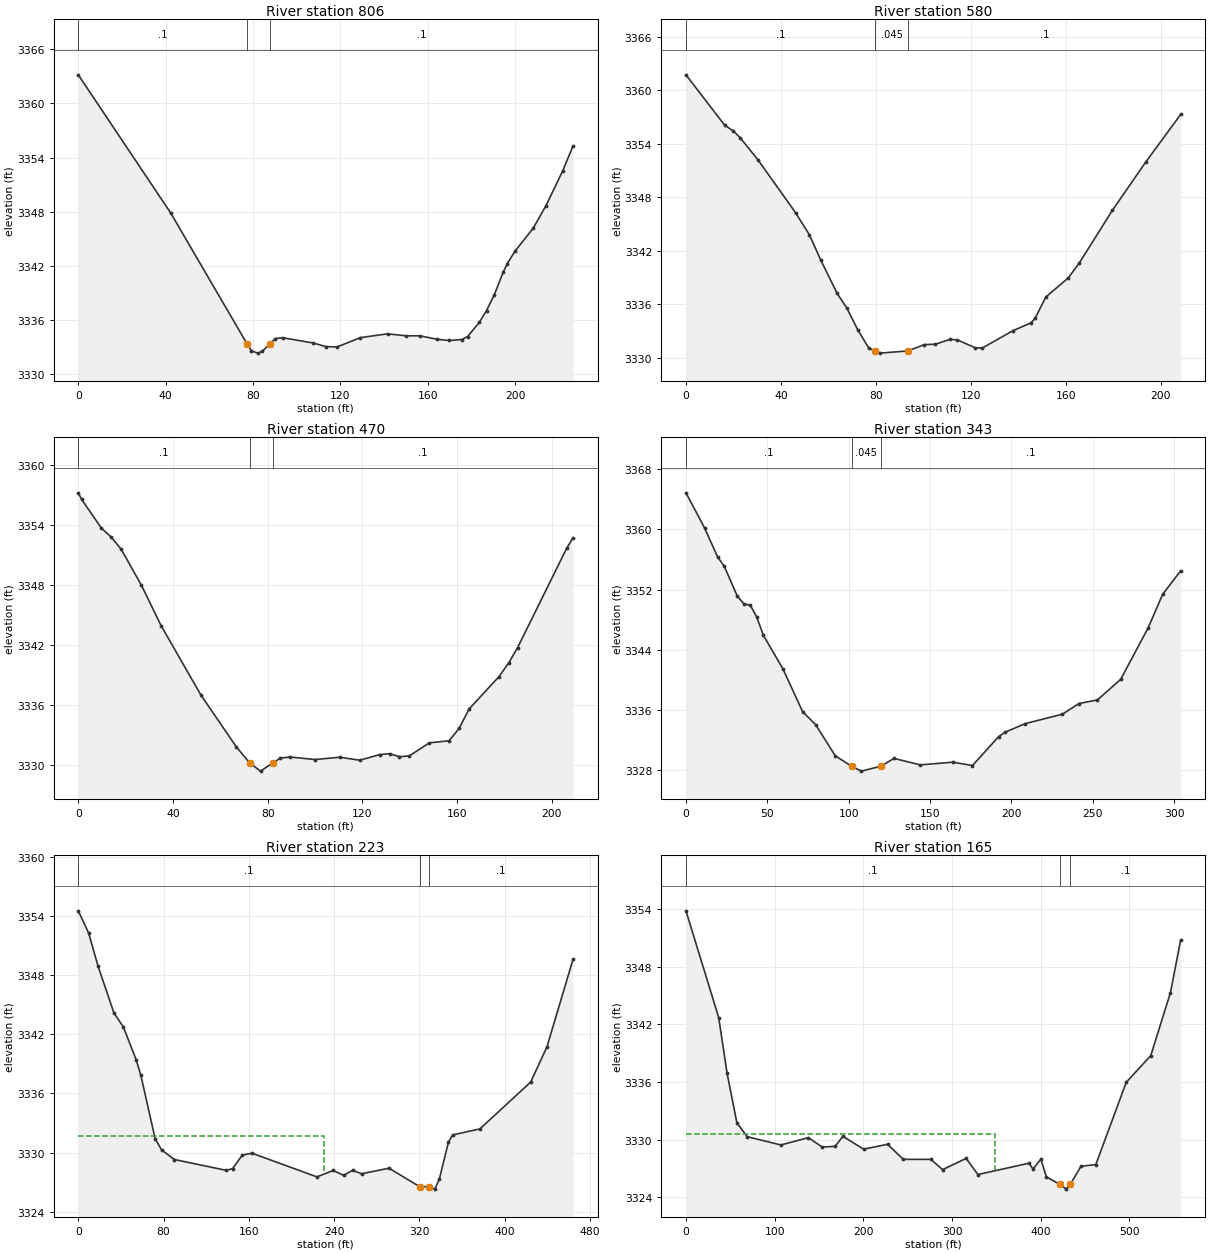
Type RM Length L Ch R = 1 ,806     ,224.1,225.3,220.8
XS GIS Cut Line= 2
2337089.16530319623750.0828372642336935.79615244623916.706112157
#Sta/Elev= 30
       0 3363.17    42.3 3347.86   77.273333.349    79.3 3332.57    82.2 3332.32
    84.2 3332.51   87.813333.354    90.1 3333.92    93.5 3334.03   107.6 3333.44
   113.3 3333.05   118.4    3333   129.2 3334.04   141.6 3334.46   150.1 3334.24
   156.4 3334.24   164.3 3333.85   169.9 3333.72   175.6 3333.83   178.2 3334.15
   183.6 3335.72   186.9 3337.04   190.5  3338.8   194.5 3341.27   196.4 3342.23
   199.9 3343.61   208.2 3346.14   214.1 3348.65   221.7 3352.48   226.5 3355.27
#Mann= 3 ,-1,0
       0      .1       0   77.27    .045       0   87.81      .1       0
Bank Sta=77.27,87.81
XS Rating Curve= 0 ,0
Exp/Cntr(USF)=0,0
Exp/Cntr=0.3,0.1

Type RM Length L Ch R = 1 ,580     ,111.1,110.3,108.4
XS GIS Cut Line= 2
2336929.45480616623611.0755848762336822.15951551623789.901069293
#Sta/Elev= 30
       0 3361.71    16.4 3356.04      20 3355.42    22.9 3354.65    30.4 3352.17
    46.2 3346.26      52  3343.8    56.9 3340.91    63.7 3337.23    67.8 3335.58
    72.4 3333.15    77.1 3331.07   79.83 3330.75    81.8 3330.53   93.573330.777
   100.4 3331.48   105.1 3331.53   111.3 3332.07   114.4 3332.01     122 3331.12
   124.9  3331.1   137.7 3333.03   145.3 3333.91   147.1 3334.41   151.7 3336.83
   161.1 3338.95   165.8 3340.64   179.7 3346.52   193.7 3351.91   208.5 3357.27
#Mann= 3 ,-1,0
       0      .1       0   79.83    .045       0   93.57      .1       0
Bank Sta=79.83,93.57
XS Rating Curve= 0 ,0
Exp/Cntr(USF)=0,0
Exp/Cntr=0.3,0.1

Type RM Length L Ch R = 1 ,470     ,129.8,126.8,124.3
XS GIS Cut Line= 3
2336812.29116241623563.7979425252336758.45859049 623733.99168912
 2336764.6700411623763.806652027
#Sta/Elev= 30
       0 3357.23     1.4 3356.58     9.8 3353.69      14 3352.78    18.2 3351.56
    26.7 3347.97      35 3343.93    51.8    3337    66.7 3331.83   72.433330.198
      77 3329.38    82.23330.208    85.4 3330.69    89.6 3330.79     100 3330.54
   110.5 3330.77   118.9 3330.47   127.3 3331.03   131.5 3331.13   135.7 3330.82
   139.9 3330.91   148.3 3332.21   156.7 3332.42   160.9 3333.66   165.1  3335.6
   177.7 3338.83   181.8 3340.19   185.6 3341.74   206.3 3351.67     209 3352.72
#Mann= 3 ,-1,0
       0      .1       0   72.43    .045       0    82.2      .1       0
Bank Sta=72.43,82.2
XS Rating Curve= 0 ,0
Exp/Cntr(USF)=0,0
Exp/Cntr=0.3,0.1

Type RM Length L Ch R = 1 ,343     ,129.1,120.4,111.8
XS GIS Cut Line= 3
2336656.95822116623513.7992790932336677.15498175623730.283306699
2336731.43377584623797.816224932
#Sta/Elev= 30
       0 3364.85    11.4 3360.21    19.5 3356.32    23.5 3355.12    31.5 3351.17
    35.5 3350.13    39.6 3349.92    43.6 3348.31    47.6 3345.93    59.6 3341.48
    71.7  3335.8    79.7 3334.07    91.8 3329.93  101.933328.535   107.8  3327.9
   119.8 3328.55   127.9 3329.59     144 3328.73   164.1 3329.09   176.1 3328.64
   192.2 3332.48   196.2 3333.07   208.4  3334.2   231.4 3335.46   241.5 3336.87
   252.9 3337.35   267.2 3340.08   284.2 3346.96     293 3351.37   304.1  3354.5
#Mann= 3 ,-1,0
       0      .1       0  101.93    .045       0   119.8      .1       0
Bank Sta=101.93,119.8
XS Rating Curve= 0 ,0
Exp/Cntr(USF)=0,0
Exp/Cntr=0.3,0.1

Type RM Length L Ch R = 1 ,223     ,57.5,57.7,58
XS GIS Cut Line= 5
2336544.28806759623508.5108835612336465.14509371623668.924967621
2336542.62940863623692.8151600552336636.03122144623728.703541332
2336711.48884361623800.480303884
#Sta/Elev= 30
       0 3354.51     9.7 3352.26    18.6 3348.89    33.4 3344.18    42.4 3342.72
    54.3 3339.42    58.7 3337.85    72.1 3331.43    78.2 3330.28    90.2 3329.31
     139 3328.21   144.9  3328.4   153.9 3329.76     163 3329.95   223.9 3327.55
   239.1  3328.2     249 3327.71   257.4 3328.21   265.9 3327.87   291.6 3328.43
  320.253326.565  329.54 3326.55   334.5 3326.31   338.8 3327.33   347.3 3331.05
   351.2  3331.8   376.8 3332.41   424.5 3337.16   439.7 3340.71   464.2 3349.58
#Mann= 3 ,-1,0
       0      .1       0  320.25    .045       0  329.54      .1       0
#XS Ineff= 2 , 0
          230.42 3331.72
Permanent Ineff=
       F       F
Bank Sta=320.25,329.54
XS Rating Curve= 0 ,0
Exp/Cntr(USF)=0,0
Exp/Cntr=0.3,0.1

Type RM Length L Ch R = 1 ,165     ,,,
XS GIS Cut Line= 3
2336511.15583893623489.4262578452336396.41299281623680.853679347
2336698.60702319623824.566253946
#Sta/Elev= 30
       0 3353.82    36.9 3342.71    46.3 3336.94    57.4 3331.75    69.1  3330.3
   106.9 3329.44   138.1  3330.2   153.6 3329.22   168.2  3329.3     177 3330.34
   200.3    3329   227.3 3329.51   245.1 3327.94   276.1 3327.94   289.4 3326.87
   315.9 3328.04   329.2 3326.36   386.8 3327.54   391.3 3326.93   400.1 3327.96
   406.4 3326.11   421.4 3325.34   428.8 3324.84   433.4 3325.35   445.4 3327.22
   462.1 3327.39   496.4 3335.96   524.1 3338.75   546.3 3345.31   557.8  3350.8
#Mann= 3 ,-1,0
       0      .1       0   421.4    .045       0   433.4      .1       0
#XS Ineff= 2 , 0
          348.63 3330.55
Permanent Ineff=
       F       F
Bank Sta=421.4,433.4
XS Rating Curve= 0 ,0
Exp/Cntr(USF)=0,0
Exp/Cntr=0.3,0.1
LCMann Table=0

Chan Stop Cuts=-1
Use User Specified Reach Order=0
Composite Channel Slope=5